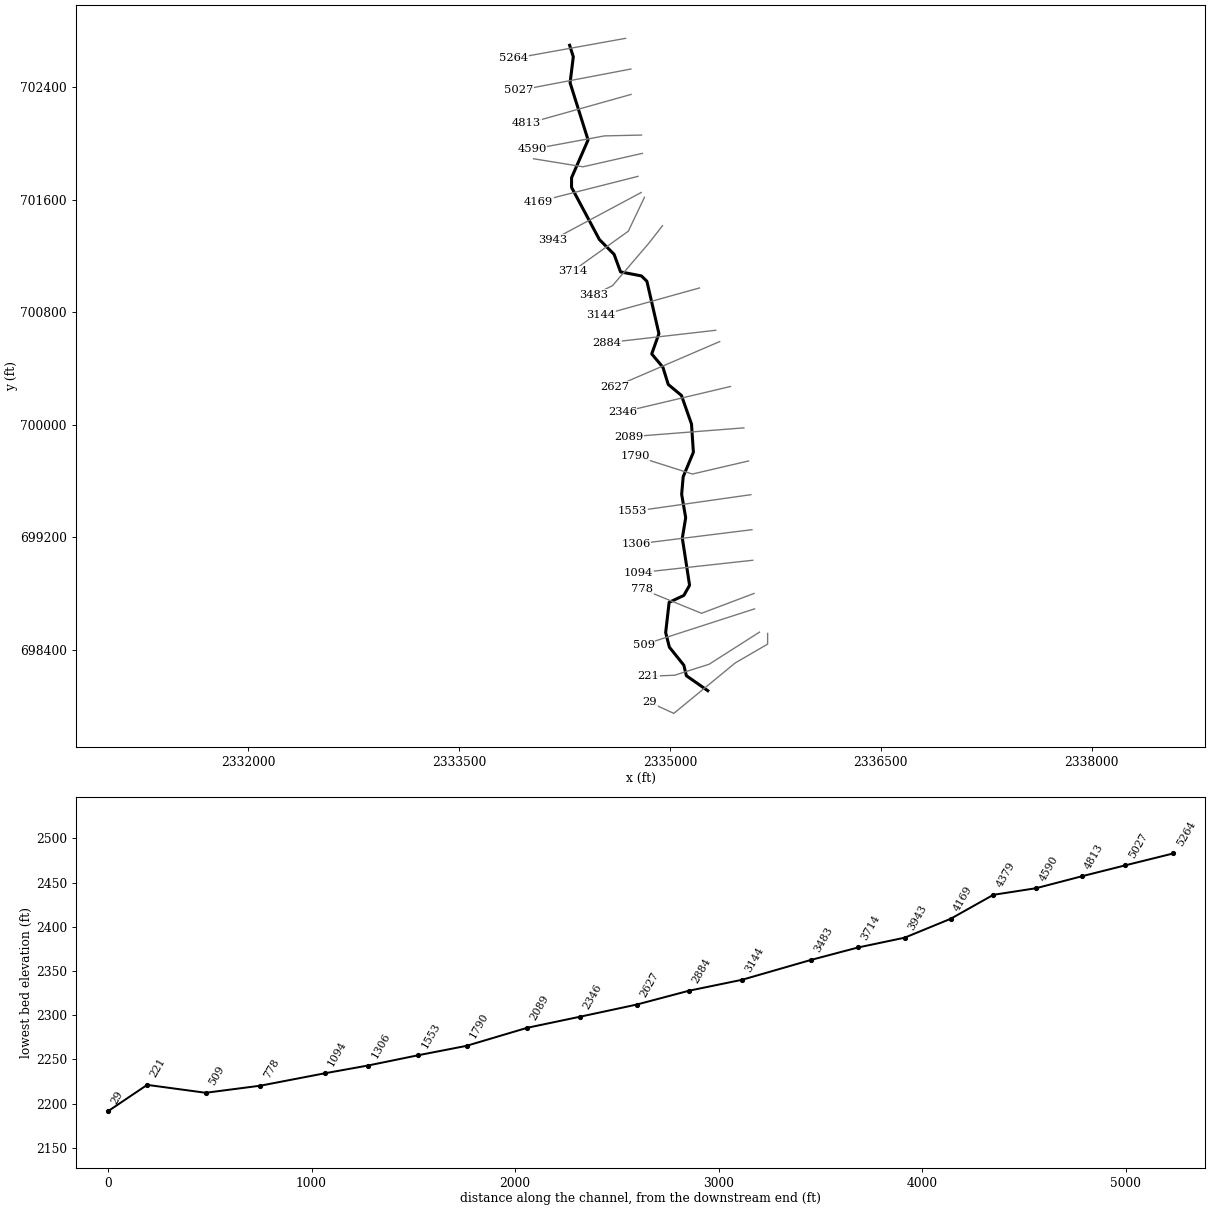
--- BCKLERN.prj (project) ---

Proj Title=BCKLERN
Current Plan=p01
Default Exp/Contr=0,0
English Units
Geom File=g01
Flow File=f01
Plan File=p01
BEGIN DESCRIPTION:
END DESCRIPTION:
DSS Export Rating Curves= 0
DSS Export Rating Curve Sorted= 0
DSS Export Volume Flow Curves= 0
DXF OffsetX= 0
DXF OffsetY= 0
DXF ScaleX= 0
DXF ScaleY= 0

--- BCKLERN.p01 (plan) ---

Plan Title=Floodplain
Program Version=4.00
Geom File=g01
Flow File=f01
K Sum by GR=0
Std Step Tol=0.01
Critical Tol=0.01
Num of Std Step Trials=20
Max Error Tol=0.3
Flow Tol Ratio=0.001
Split Flow NTrial=30
Split Flow Tol=0.02
Split Flow Ratio=0.02
Log Output Level=0
Friction Slope Method=1
Unsteady Friction Slope Method=2
Unsteady Bridges Friction Slope Method=1
Global Log Level=0
CheckData=False
Run HTab=0
Run UNet=0
Run PostProcess=0
UNET Theta=0
UNET Theta Warmup=0
UNET ZTol=0
UNET ZSATol=0
UNET MxIter=0
UNET MaxInSteps=0
UNET DtIC=0
UNET DtMin=0
UNET MaxCRTS=0
UNET WFStab=0
UNET SFStab=0
UNET WFX=0
UNET SFX=0
UNET DSS MLevel=0
UNET DZMax Abort=0
UNET Convert EG Bridges=0
UNET Use Existing IB Tables=0
UNET Froude Limit=0
UNET Froude Power=0
Write IC File=0
Echo Input=False
Echo Output=False
Write Detailed=0

--- BCKLERN.f01 (steady flow) ---

Flow Title=Flow
Program Version=4.00
Number of Profiles=1
Profile Names=P100yr
River Rch & RM=BCKLERN,Main      ,5275.9
293.0493
River Rch & RM=BCKLERN,Main      ,4775.9
309.0687
River Rch & RM=BCKLERN,Main      ,4275.9
366.5706
Boundary for River Rch & Prof#=BCKLERN,Main      ,1
Up Type=0
Dn Type=3
Dn Slope=0.068254

--- BCKLERN.g01 (geometry) ---

Geom Title=Geometry
Program Version=6.20

River Reach=BCKLERN         ,Main
Reach XY= 30
     2334286.043      702699.493     2334312.161      702617.699
     2334289.405      702432.255     2334417.293      702025.882
     2334299.932      701757.479     2334299.585      701688.729
     2334497.675      701317.462     2334602.276      701212.427
     2334648.283      701087.427     2334796.286      701058.781
     2334835.783      701020.587     2334921.286      700648.191
     2334870.071       700503.66     2334949.498      700409.042
     2334987.692      700286.212     2335081.443      700208.521
     2335153.057      700004.962     2335166.382      699804.152
     2335093.812      699630.193     2335083.048      699504.846
     2335111.694      699338.657     2335087.714      699193.391
     2335139.363      698858.105     2335098.565      698785.839
     2334993.906      698736.302     2334969.254      698521.719
     2334995.643      698417.552     2335098.333      698289.557
     2335116.563       698214.47     2335268.891      698108.095

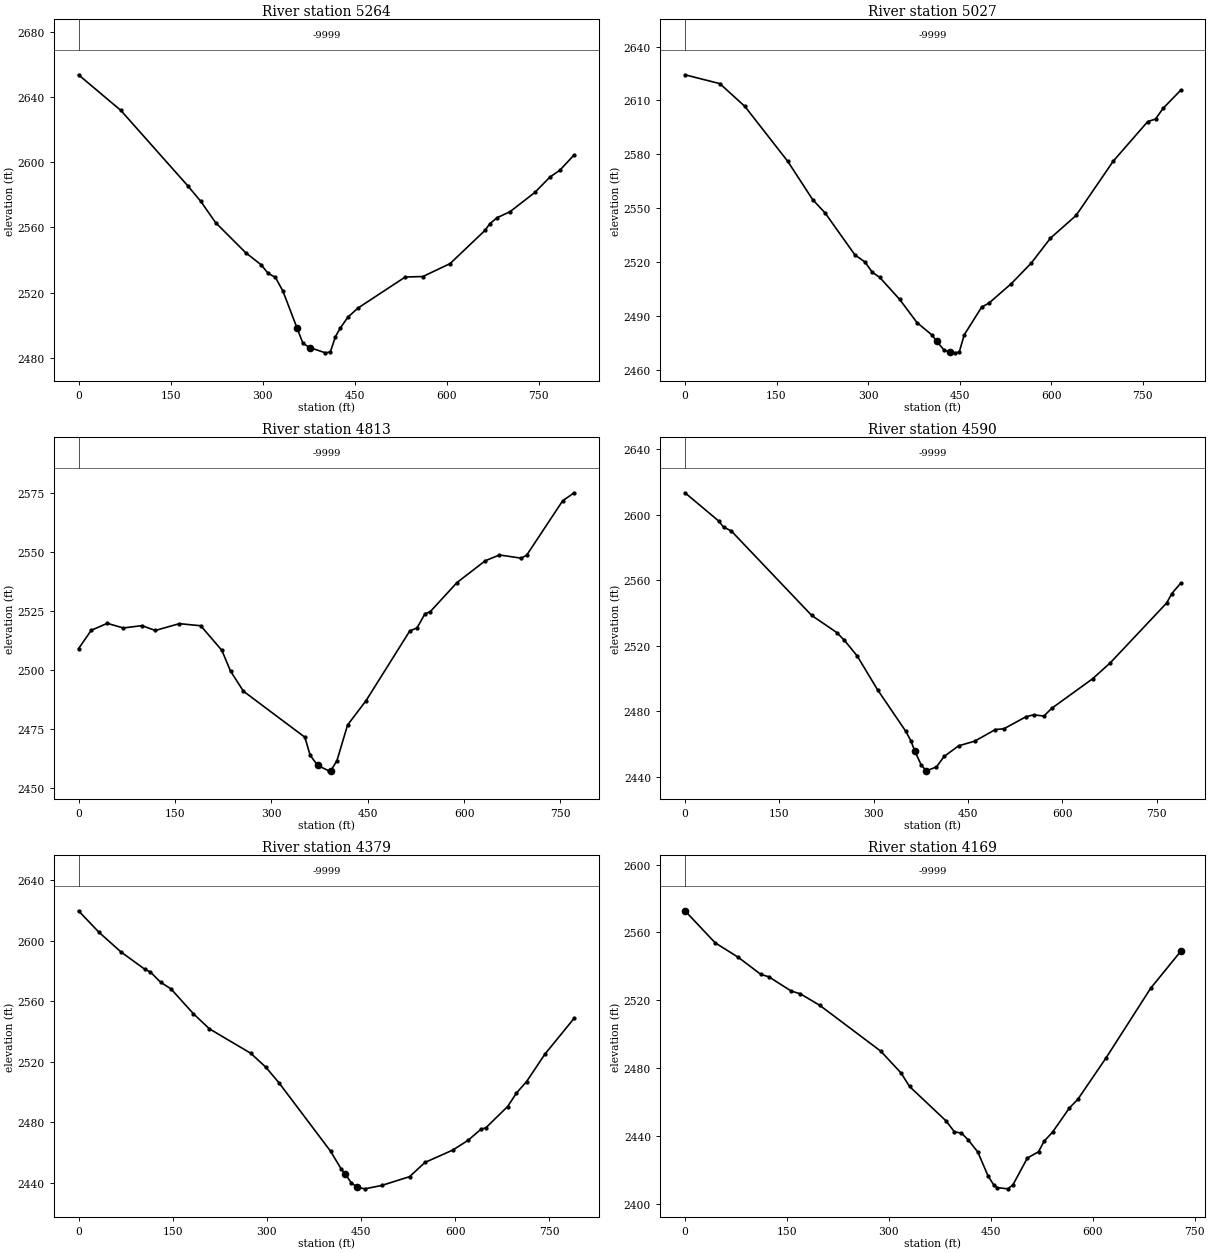
Type RM Length L Ch R = 1 ,5264    ,236.5,236.5,236.5
XS GIS Cut Line= 2
2334684.12723317702748.7797963582333889.18690585702605.750760192
#Sta/Elev= 30
       0 2653.77      69 2631.88   178.8 2585.28   199.1 2576.11   223.5 2562.96
   272.3 2544.56   297.8 2537.04   308.8 2531.91     321  2529.3   333.2 2520.85
   356.32498.074   365.7  2488.9   376.72486.283   402.3 2483.03   410.4 2483.57
   418.6  2492.9   426.7  2498.3   438.9 2504.91   455.1 2510.44   532.4 2529.59
   561.1 2529.88   605.5 2537.82   662.4 2558.23   670.5 2562.43   682.7 2566.11
   703.1 2569.67   743.7 2581.54   768.1 2590.92   784.3 2595.13   807.7 2604.61
#Mann= 1 ,-1,0
       0   -9999       0
Bank Sta=356.3,376.7
XS Rating Curve= 0 ,0
Exp/Cntr(USF)=0,0
Exp/Cntr=0.3,0.1

Type RM Length L Ch R = 1 ,5027    ,214.4,214.4,214.4
XS GIS Cut Line= 2
2334721.76645322702530.4723201052333923.81498829702378.409871129
#Sta/Elev= 30
       0 2624.28    57.2 2619.34    98.2 2606.67   168.6 2576.02   209.3 2554.79
   229.7 2547.36   278.5 2524.04   294.8 2520.12     307  2514.4   319.2 2511.51
   351.8 2499.28   380.3 2486.35   404.7 2479.49   412.42476.008   425.1 2470.88
     4342470.163   443.1 2469.54   449.5 2469.99   457.7  2479.6   486.2 2494.97
   498.4 2497.28     535 2508.11   567.6 2519.53     599 2533.37   640.9 2545.98
     702 2576.28   758.3 2598.21   771.2 2599.66   783.4 2605.55   812.3 2615.65
#Mann= 1 ,-1,0
       0   -9999       0
Bank Sta=412.4,434
XS Rating Curve= 0 ,0
Exp/Cntr(USF)=0,0
Exp/Cntr=0.3,0.1

Type RM Length L Ch R = 1 ,4813    ,223.4,223.4,223.4
XS GIS Cut Line= 3
2334723.27202202702349.8040638962334020.17139161702152.574550868
2333979.52103396702146.552275661
#Sta/Elev= 30
       0 2508.99    19.8 2516.81    44.8 2519.77    69.7  2517.8    98.8 2518.79
   119.5 2516.74   156.9 2519.63   190.2 2518.74     223 2508.32   236.6 2499.45
   256.6 2490.94   352.2  2471.4   360.5 2463.72   372.22459.401   389.6 2457.11
   392.62457.161   402.1  2461.4   418.7 2476.59   447.5 2486.95   515.6 2516.59
   526.7 2517.78   539.1 2523.82   547.4 2524.74     589  2537.1   632.9 2546.35
   655.1 2548.81   688.7 2547.46   697.3 2548.68   753.4 2571.83   771.3 2575.23
#Mann= 1 ,-1,0
       0   -9999       0
Bank Sta=372.2,392.6
XS Rating Curve= 0 ,0
Exp/Cntr(USF)=0,0
Exp/Cntr=0.3,0.1

Type RM Length L Ch R = 1 ,4590    ,210.7,210.7,210.7
XS GIS Cut Line= 3
2334797.55409269702060.734853962  2334533.570353702054.712578755
2334018.37485173701959.861744245
#Sta/Elev= 30
       0 2613.27    53.4 2596.13    61.4 2592.33    73.4 2590.07   201.4 2538.48
   241.4 2528.01   253.4 2523.31   273.6 2513.83   306.1 2493.16   350.9 2467.85
     359 2462.11   365.2 2455.84   375.3 2447.43   383.4 2443.69   383.92443.706
   399.7 2446.06   411.9 2452.44   434.9 2458.92   460.7 2461.82   493.4 2468.88
     507 2469.36     542 2476.66   554.2 2477.87   570.5 2477.09   582.9  2481.8
   648.1 2499.88   676.3 2509.65   765.7 2546.07   773.9 2551.79   787.9 2558.13
#Mann= 1 ,-1,0
       0   -9999       0
Bank Sta=365.2,383.9
XS Rating Curve= 0 ,0
Exp/Cntr(USF)=0,0
Exp/Cntr=0.3,0.1

Type RM Length L Ch R = 1 ,4379    ,209.9,209.9,209.9
XS GIS Cut Line= 3
2334803.64911067701930.6122667652334381.50790402  701834.8995337
2334029.48476082701892.183890936
#Sta/Elev= 30
       0 2619.63    32.3 2605.56    67.6 2592.48   106.1 2580.89   114.3  2579.3
   130.7 2572.49   147.1 2568.17     183  2551.7   208.6 2541.71   274.3 2525.62
   298.3 2516.45   319.4 2506.09   401.4 2461.03   418.7 2449.06     4252445.853
   434.2 2440.28   443.52437.294   455.9 2436.16   482.8 2438.38   527.4  2444.2
   551.7 2453.55   596.3 2461.77   620.5 2468.17   640.9 2475.44     649  2476.5
   683.5 2490.47   697.6 2499.37   713.8 2506.98   742.7 2524.93   789.5 2548.72
#Mann= 1 ,-1,0
       0   -9999       0
Bank Sta=425,443.5
XS Rating Curve= 0 ,0
Exp/Cntr(USF)=0,0
Exp/Cntr=0.3,0.1

Type RM Length L Ch R = 1 ,4169    ,226.1,226.1,226.1
XS GIS Cut Line= 2
2334772.33415159701766.9307093142334065.55897869701587.942191503
#Sta/Elev= 30
       0 2572.79    44.4 2553.92    78.6 2545.34   111.6 2535.31   123.4  2533.9
   156.3  2525.5   169.5 2523.92   198.2 2517.13     288 2490.11   317.9 2477.24
   330.3 2469.32   383.9 2449.09   396.3 2442.62   406.7 2441.85   416.9 2437.74
   430.8 2430.66   445.8 2416.64   454.1  2411.4   459.2 2409.77   474.7 2409.03
   482.3 2411.31   503.6 2427.15   520.1 2430.89   528.3 2437.09   540.7 2442.43
   565.5 2456.67   577.8 2461.72   619.1 2485.97   685.1 2527.22729.0871 2548.85
#Mann= 1 ,-1,0
       0   -9999       0
Bank Sta=0,729.0871
XS Rating Curve= 0 ,0
Exp/Cntr(USF)=0,0
Exp/Cntr=0.3,0.1

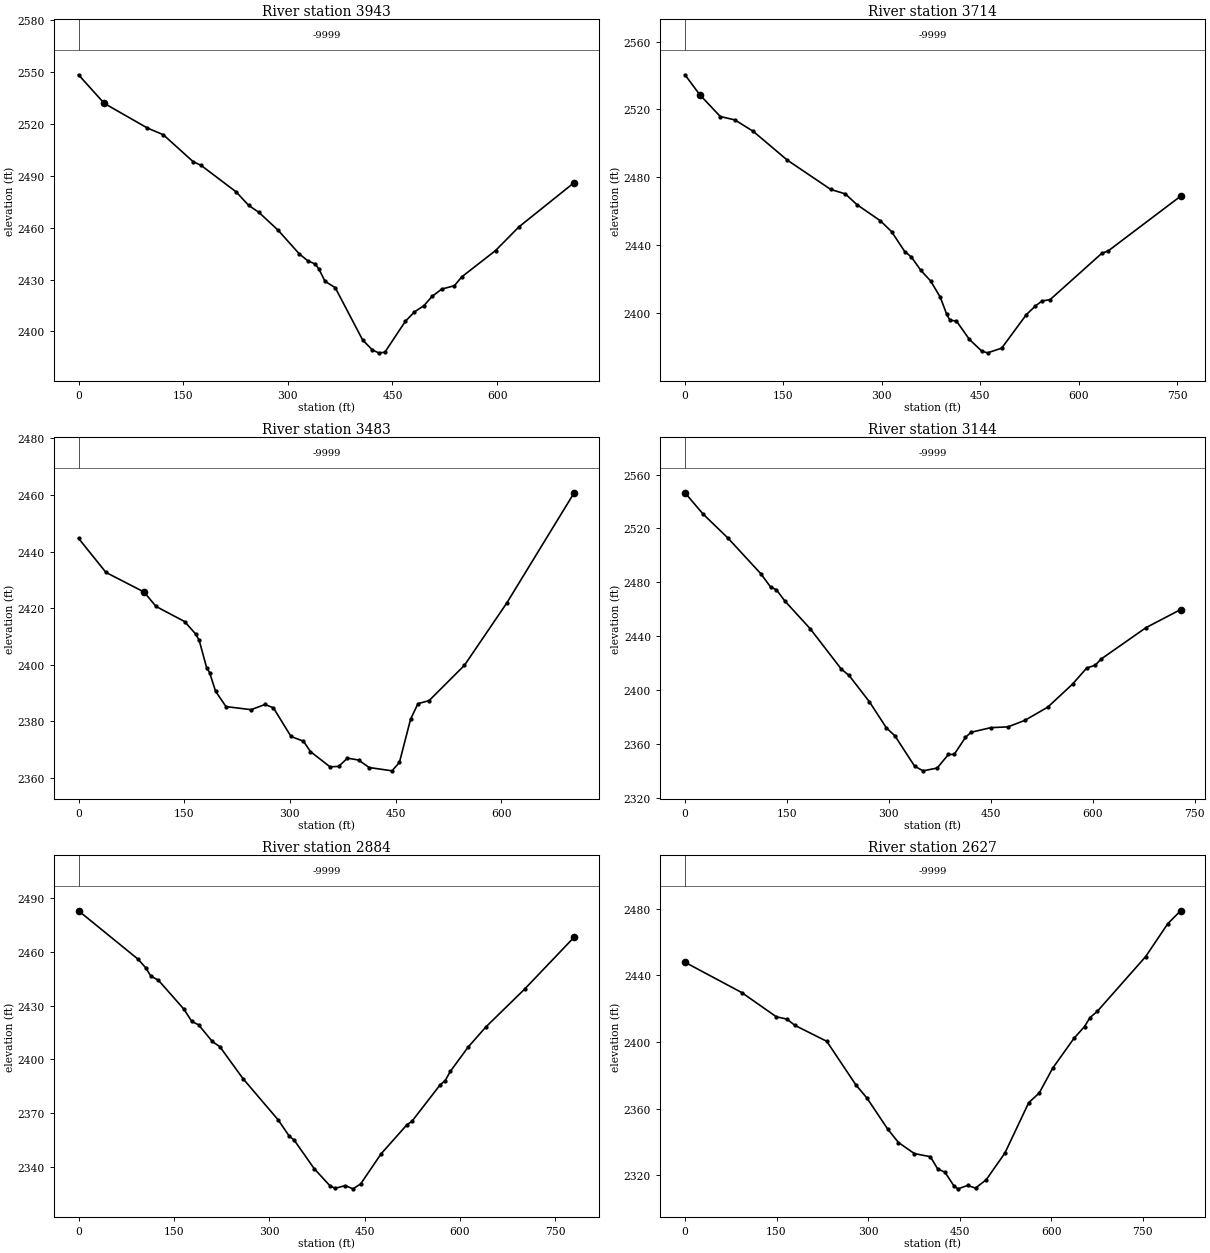
Type RM Length L Ch R = 1 ,3943    ,228.7,228.7,228.7
XS GIS Cut Line= 2
2334795.28139746701652.1944799482334168.82158512701317.164690199
#Sta/Elev= 30
       0 2548.5536.845942532.016    98.8 2517.72   121.5 2513.87   164.1 2498.34
   175.9 2496.07   226.2 2480.69   243.9 2472.96   258.7 2468.88   286.3 2458.51
   316.5 2444.87   328.7 2440.89   339.2 2439.05   344.4 2436.26   353.3 2429.07
     368 2425.32   407.2 2395.12   421.2 2389.31   430.1 2387.64     439 2387.94
   468.5  2405.9   481.4 2411.28   495.1 2414.95   506.8  2420.3   520.6 2424.52
   538.8  2426.5   549.2 2431.56   597.8 2446.85   631.1 2460.48710.4202 2486.15
#Mann= 1 ,-1,0
       0   -9999       0
Bank Sta=36.84594,710.4202
XS Rating Curve= 0 ,0
Exp/Cntr(USF)=0,0
Exp/Cntr=0.3,0.1

Type RM Length L Ch R = 1 ,3714    ,230.8,230.8,230.8
XS GIS Cut Line= 3
2334818.22864333701617.7736111382334703.49241397701376.827529469
2334306.50506036701092.281680641
#Sta/Elev= 30
       0 2540.4322.494012528.714    53.8 2515.84      76 2513.84     104  2507.1
   155.7 2490.21   222.2 2472.84   244.3 2470.26     262 2463.92   297.7 2454.41
   314.9 2447.98   334.9 2436.25   344.8 2433.13   359.5 2425.13   374.3 2418.95
   389.1 2409.35   398.9 2399.23   403.7 2395.85   413.7  2395.3   433.4  2384.5
   452.5  2377.5   461.1 2376.58   482.6 2379.35   520.3 2399.15     534 2404.21
   544.2 2407.14   556.4 2407.93   635.1  2435.2     645 2436.66755.3011  2468.9
#Mann= 1 ,-1,0
       0   -9999       0
Bank Sta=22.49401,755.3011
XS Rating Curve= 0 ,0
Exp/Cntr(USF)=0,0
Exp/Cntr=0.3,0.1

Type RM Length L Ch R = 1 ,3483    ,339.1,339.1,339.1
XS GIS Cut Line= 4
2334946.73322022701415.8378474532334848.06006297701289.627995151
2334591.05090919700989.0190742112334457.95688312700924.766785767
#Sta/Elev= 30
       0 2444.73    38.9 2432.6793.052422425.729     110 2420.64   150.6 2415.29
   166.1 2410.95   171.3 2408.65   181.8 2399.02     186 2397.28   194.5 2390.68
   209.3 2385.24     245 2384.15   264.7 2385.99   276.6  2384.8   301.6 2374.68
   319.3    2373   329.2 2369.33     357 2363.94   369.3 2364.11   381.7 2367.02
   397.6 2366.34   412.4 2363.71     445 2362.53   455.5 2365.53   471.3 2380.77
   481.8 2386.27   497.6 2387.35   547.8 2399.84   607.8 2421.84703.4946 2460.81
#Mann= 1 ,-1,0
       0   -9999       0
Bank Sta=93.05242,703.4946
XS Rating Curve= 0 ,0
Exp/Cntr(USF)=0,0
Exp/Cntr=0.3,0.1

Type RM Length L Ch R = 1 ,3144    ,260,260,260
XS GIS Cut Line= 2
2335209.70224391700973.0807232122334507.10346977700777.356778986
#Sta/Elev= 30
       0 2546.45    26.5 2530.73    62.9 2513.01   111.6 2486.36   126.2 2476.36
   134.5 2474.48   146.9 2466.14   184.3  2445.5     230 2415.59   241.5 2410.82
   271.5 2391.22   296.4  2371.9   308.9 2366.04   337.9 2343.49   350.4 2340.03
   371.1  2342.1   387.7 2352.24   396.1 2352.19   412.7 2364.83     421 2368.67
     450 2372.07   475.3 2372.68   499.9 2377.45   533.8  2387.3   570.5 2404.51
   591.2 2416.41   603.7 2418.39     612  2422.9   678.4 2446.33 729.351 2459.76
#Mann= 1 ,-1,0
       0   -9999       0
Bank Sta=0,729.351
XS Rating Curve= 0 ,0
Exp/Cntr(USF)=0,0
Exp/Cntr=0.3,0.1

Type RM Length L Ch R = 1 ,2884    ,257.5,257.5,257.5
XS GIS Cut Line= 2
2335325.12918538700671.966962864 2334550.5976796700583.305688984
#Sta/Elev= 30
       0 2483.09    93.6 2456.05   105.6 2451.27   113.7 2446.61   125.8 2444.23
     166 2428.01   178.1 2421.26   188.9 2419.36   210.3  2410.1   222.4 2407.08
   258.6 2389.34   314.1  2366.2   331.1 2357.34   339.4 2354.82   370.7 2338.98
   395.5  2329.4   403.6    2328   419.7  2329.5   431.8  2327.7   443.8 2330.46
     476  2347.3   516.3 2363.41   524.4 2365.43   568.6 2385.74   576.7 2388.15
   584.7 2393.29   612.9 2406.96   641.1 2418.31   701.5 2439.26779.5895 2468.35
#Mann= 1 ,-1,0
       0   -9999       0
Bank Sta=0,779.5895
XS Rating Curve= 0 ,0
Exp/Cntr(USF)=0,0
Exp/Cntr=0.3,0.1

Type RM Length L Ch R = 1 ,2627    ,281,281,281
XS GIS Cut Line= 2
2335353.56770719700591.6699601052334607.47472322700270.481949066
#Sta/Elev= 30
       0 2447.84      93 2429.68   149.6 2415.18     167 2413.76   180.1 2410.02
   232.3 2400.45   280.2 2374.26   298.3 2366.39   332.5 2347.68   349.9 2339.77
     376 2333.12   402.2 2331.26   413.9 2324.06   426.1 2321.91   441.3 2313.47
   447.4 2311.99   463.1 2314.01   476.2 2312.45   493.6 2317.42   524.1  2333.3
   563.3 2363.63   580.7 2369.52   602.5 2384.26   637.3 2402.15   654.8 2409.32
   663.8 2414.69   675.8 2418.45   754.9 2451.21   791.4 2471.05812.2909 2478.71
#Mann= 1 ,-1,0
       0   -9999       0
Bank Sta=0,812.2909
XS Rating Curve= 0 ,0
Exp/Cntr(USF)=0,0
Exp/Cntr=0.3,0.1

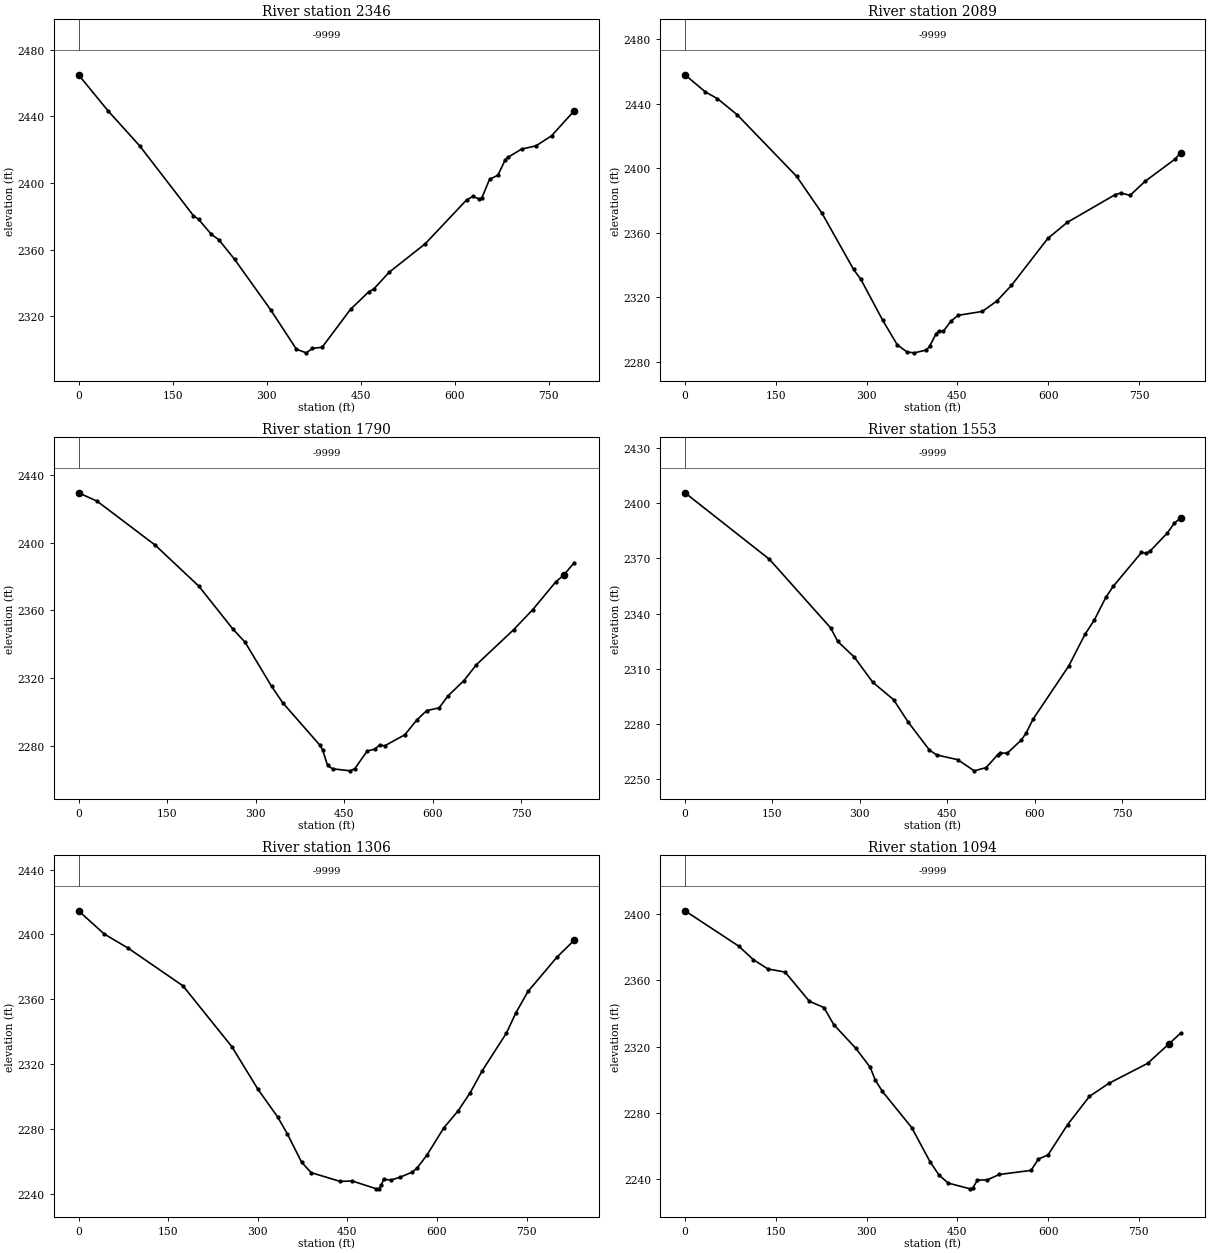
Type RM Length L Ch R = 1 ,2346    ,257.2,257.2,257.2
XS GIS Cut Line= 2
 2335430.5190015 700272.154803292334661.00605839700089.813692857
#Sta/Elev= 30
       0 2464.96    47.6 2443.12    97.5 2422.37   183.3 2380.49   191.5 2378.26
   212.1 2369.18   223.8 2366.02   249.1 2354.19   306.6 2323.92   347.7  2300.3
   363.3 2298.13   373.3 2300.78   388.8 2301.52     434 2324.24   462.8 2334.66
     471 2336.41   495.7 2346.51   553.3  2363.6   619.2  2389.9   629.2 2391.94
   639.6 2390.41   643.7 2391.24   655.8 2402.22   669.1 2404.69   680.7 2413.81
   684.8 2415.35   706.8 2420.34     730 2422.34   754.7 2428.34790.8214  2443.3
#Mann= 1 ,-1,0
       0   -9999       0
Bank Sta=0,790.8214
XS Rating Curve= 0 ,0
Exp/Cntr(USF)=0,0
Exp/Cntr=0.3,0.1

Type RM Length L Ch R = 1 ,2089    ,298.1,298.1,298.1
XS GIS Cut Line= 2
2335525.87169228699977.7324598392334709.51883089699914.163999321
#Sta/Elev= 30
       0 2457.95    33.8 2447.29    53.5  2443.2      86 2433.28   184.5    2395
   226.4 2372.17   278.5 2337.39   290.6  2331.2   326.7 2305.82   350.8 2290.62
   366.9 2286.22   378.8  2285.7   398.9 2287.45   404.1 2289.79   414.9 2297.53
   418.9 2299.05     427 2299.19     439 2305.14   451.1 2308.94   491.2 2311.34
   515.3  2317.8   539.3 2327.46   599.5 2356.61   631.6 2366.53   710.4 2383.64
   719.9 2384.71   735.4 2383.26     760 2391.92   809.8 2405.77818.8241 2409.68
#Mann= 1 ,-1,0
       0   -9999       0
Bank Sta=0,818.8241
XS Rating Curve= 0 ,0
Exp/Cntr(USF)=0,0
Exp/Cntr=0.3,0.1

Type RM Length L Ch R = 1 ,1790    ,237.2,237.2,237.2
XS GIS Cut Line= 3
2335558.81107556699742.1907662022335159.18478868699649.254420416
2334750.26486722699779.365304517
#Sta/Elev= 30
       0 2429.47    31.5  2424.5   129.7  2398.6   203.9 2374.28   261.4 2349.02
     282 2341.28   327.1  2315.1   346.2 2305.32   408.9 2280.38   413.4 2277.63
   421.8 2268.49   430.2 2266.49   460.4 2265.28     468 2266.61     489 2277.01
   501.6 2278.06     510 2280.57   518.4 2280.04   552.7 2286.59     573 2295.37
   589.7 2300.86   610.7 2302.46     626 2309.65   652.7 2318.55   673.7 2327.91
   736.7 2348.55   769.3 2360.49     808 2376.76821.69872380.875   839.4 2388.16
#Mann= 1 ,-1,0
       0   -9999       0
Bank Sta=0,821.6987
XS Rating Curve= 0 ,0
Exp/Cntr(USF)=0,0
Exp/Cntr=0.3,0.1

Type RM Length L Ch R = 1 ,1553    ,247,247,247
XS GIS Cut Line= 3
2335575.53961781699502.4149940732334765.13468255699387.173925298
2334733.53632498699383.456471466
#Sta/Elev= 30
       0 2405.52   144.8 2369.46   249.9 2332.23     262 2324.91   290.3 2316.43
   322.4 2302.66   357.8 2293.32   383.2 2281.01   419.5 2265.91   431.7 2263.33
     468 2260.71   496.3 2254.67   516.5 2256.41   536.7 2263.43   540.8 2264.38
   552.9 2264.22   577.1 2271.41   585.2 2275.11   597.3 2282.76   658.5 2311.61
   686.2 2328.66   702.4 2336.55   722.1 2348.79   734.7 2354.76   783.2 2373.15
   791.2 2372.67   798.5 2374.07   827.6 2383.72   839.2 2388.89 850.374 2391.93
#Mann= 1 ,-1,0
       0   -9999       0
Bank Sta=0,850.374
XS Rating Curve= 0 ,0
Exp/Cntr(USF)=0,0
Exp/Cntr=0.3,0.1

Type RM Length L Ch R = 1 ,1306    ,212.3,212.3,212.3
XS GIS Cut Line= 2
2335582.97452547699253.345587365 2334759.5585018   699151.115607
#Sta/Elev= 30
       0 2414.61    43.1 2400.27    83.4 2391.47   174.8 2368.31   256.8  2330.7
   300.3 2304.51   333.3 2287.41   349.5 2277.03   373.6 2259.36   389.6    2253
   438.1  2247.6   458.3 2247.87   498.6 2243.02   502.6 2243.08   506.7 2245.12
   510.7 2248.95   522.8  2248.4   538.9 2250.27   559.1 2253.42   567.1 2255.99
   583.5 2263.98   611.5 2280.63   635.6 2291.22   655.8 2302.42   675.9 2315.94
   716.3 2339.12   732.4 2351.78   752.5 2364.86   800.9 2385.99829.7379 2396.43
#Mann= 1 ,-1,0
       0   -9999       0
Bank Sta=0,829.7379
XS Rating Curve= 0 ,0
Exp/Cntr(USF)=0,0
Exp/Cntr=0.3,0.1

Type RM Length L Ch R = 1 ,1094    ,316,316,316
XS GIS Cut Line= 2
2335588.55070622699035.8745382252334774.42831713698946.655646269
#Sta/Elev= 30
       0 2401.94    88.9  2380.6     113 2372.44   137.2 2366.83   165.4 2364.98
   205.6 2347.34   229.7 2343.56   245.8 2333.29   282.1 2319.06   306.2 2307.46
   314.2 2299.99   326.3 2292.94   374.6 2271.19   405.3 2250.32   419.8 2242.53
     435 2237.67   471.2 2234.22   475.2 2234.52   483.3 2239.51   499.3  2239.6
   519.5 2242.88   571.8 2245.35   583.9 2252.17   599.9 2254.69   632.1 2272.91
   668.4    2290   700.5 2297.86   764.4 2309.88800.31742321.863     819  2328.1
#Mann= 1 ,-1,0
       0   -9999       0
Bank Sta=0,800.3174
XS Rating Curve= 0 ,0
Exp/Cntr(USF)=0,0
Exp/Cntr=0.3,0.1

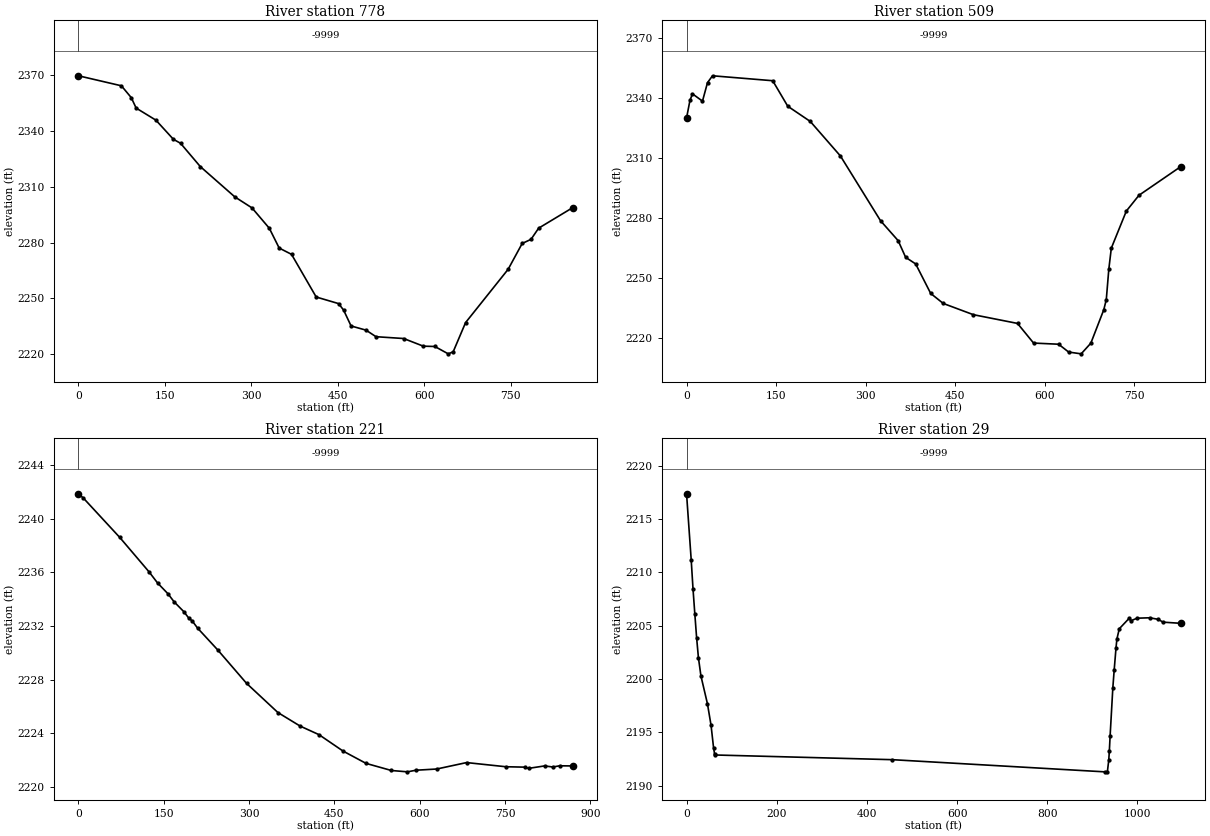
Type RM Length L Ch R = 1 ,778     ,269,269,269
XS GIS Cut Line= 3
2335597.84434079698799.8162199272335224.24023073698658.552974331
2334800.45049395698831.414577494
#Sta/Elev= 30
       0 2369.81    74.5 2364.42    91.6 2358.07   100.1 2352.43   134.4 2345.93
   164.7 2335.64   177.1  2333.5   211.3 2320.99   271.2 2304.67   301.1 2298.72
   331.1 2287.77   348.2 2277.13   369.6 2273.75   412.4 2250.79   451.3 2247.24
     460 2243.71   472.9 2235.21   498.8 2232.97   516.1 2229.44   564.1 2228.46
   598.2 2224.35   618.2 2224.17   641.4 2220.22     650 2221.32   671.5 2237.03
   745.3  2265.7   769.7 2279.61     785 2281.81   798.2 2287.82857.1074 2298.83
#Mann= 1 ,-1,0
       0   -9999       0
Bank Sta=0,857.1074
XS Rating Curve= 0 ,0
Exp/Cntr(USF)=0,0
Exp/Cntr=0.3,0.1

Type RM Length L Ch R = 1 ,509     ,287.5,287.5,287.5
XS GIS Cut Line= 2
2335601.56179463698690.1513318992334813.46158236698435.505744443
#Sta/Elev= 30
       0 2329.97     5.7 2338.72     9.9    2342    26.7 2338.36    35.1 2347.59
    43.5 2351.02   144.4 2348.55   169.6 2335.82   207.4 2328.21   257.9 2310.97
   325.1 2278.65   354.6 2268.71   367.2 2260.37     384 2257.07   409.2 2242.34
   430.2 2237.34   480.7 2231.73   554.7 2227.37   581.6 2217.56   623.6 2216.98
   640.4 2213.07   661.4 2212.18   677.6 2217.51   699.3 2234.21   703.5 2239.27
   707.7 2254.37   711.9 2264.94   737.1 2283.48   758.3 2291.36828.2188 2305.65
#Mann= 1 ,-1,0
       0   -9999       0
Bank Sta=0,828.2188
XS Rating Curve= 0 ,0
Exp/Cntr(USF)=0,0
Exp/Cntr=0.3,0.1

Type RM Length L Ch R = 1 ,221     ,192.4,192.4,192.4
XS GIS Cut Line= 4
2335636.87760603698524.7246363992335278.14331129698296.101225764
2335032.79135841698218.0346953032334846.91866684 698210.59978764
#Sta/Elev= 30
       0 2241.85     8.9 2241.52    72.6  2238.6   124.2 2236.03   139.2  2235.2
   157.4  2234.4   168.2  2233.8   185.2 2233.07   194.3 2232.57     200 2232.38
   209.5 2231.84   244.8 2230.22   295.7 2227.72   350.7 2225.55   389.8 2224.54
     423  2223.9   465.2 2222.68   505.7 2221.76   550.3 2221.23   578.6 2221.13
   593.3 2221.25   629.9 2221.34   682.5 2221.82   751.5 2221.51   784.4 2221.48
   791.6 2221.39   819.6 2221.57   834.4 2221.49   845.9 2221.58868.8863 2221.57
#Mann= 1 ,-1,0
       0   -9999       0
Bank Sta=0,868.8863
XS Rating Curve= 0 ,0
Exp/Cntr(USF)=0,0
Exp/Cntr=0.3,0.1

Type RM Length L Ch R = 1 ,29      ,,,
XS GIS Cut Line= 5
2335694.49814041 698515.431001822335694.49814041698439.223198275
2335464.01600286698305.3948603422335027.21517767697946.660565606
2334856.21230142698024.727096067
#Sta/Elev= 30
       0 2217.38    10.3 2211.18    14.3 2208.47    18.3 2206.13    22.3 2203.88
    26.3 2202.01    31.9 2200.29    46.3 2197.69    54.3 2195.67    59.9 2193.56
    62.3 2192.94    63.9 2192.88   456.5 2192.44   927.2  2191.3   933.3 2191.31
   936.3 2192.37   937.7 2193.27   939.3 2194.62   945.4 2199.18   948.4 2200.85
   952.5 2202.95   954.4 2203.75   959.7 2204.72   981.4 2205.69     986 2205.48
   999.2 2205.71  1026.9 2205.75  1046.6  2205.6  1056.4 2205.341095.936 2205.23
#Mann= 1 ,-1,0
       0   -9999       0
Bank Sta=0,1095.936
XS Rating Curve= 0 ,0
Exp/Cntr(USF)=0,0
Exp/Cntr=0.3,0.1
LCMann Table=0

Chan Stop Cuts=-1
Use User Specified Reach Order=0
Composite Channel Slope=5