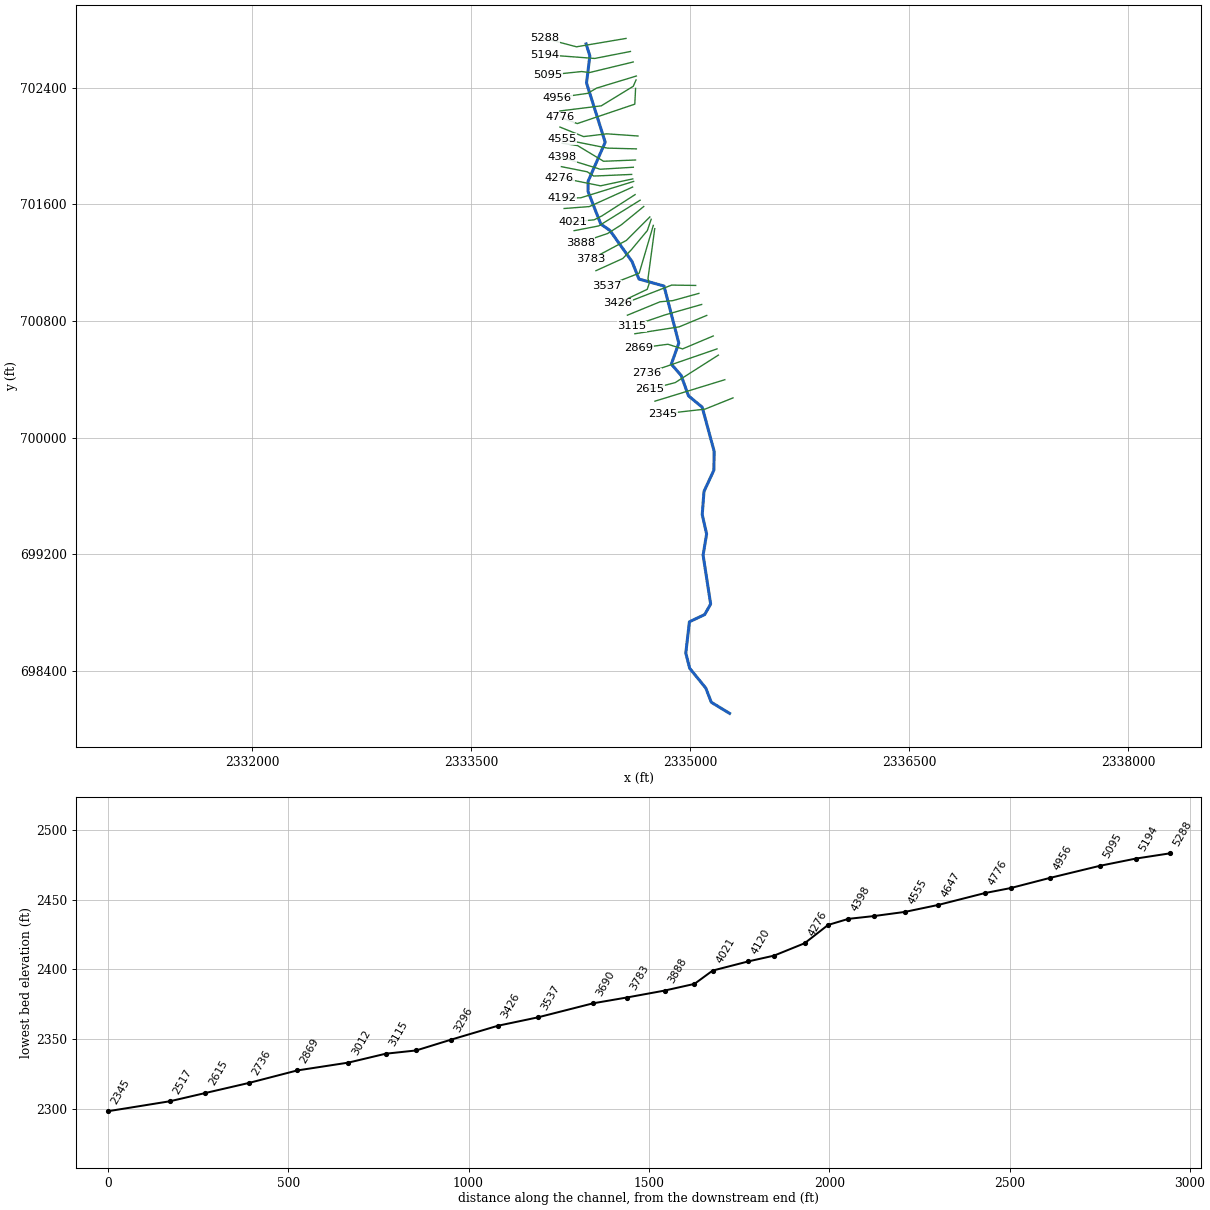
--- BCKLERN.prj (project) ---

Proj Title=BCKLERN
Current Plan=p01
Default Exp/Contr=0,0
English Units
Geom File=g01
Flow File=f01
Plan File=p01
BEGIN DESCRIPTION:
----------MODEL BY WOOD PLC 2022----------
AFH study
Randolph County, WV
HEC-RAS Version: RAS 6.2
Vertical Datum: NAVD88
Projection: NAD 1983 StatePlane West Virginia S FIPS 4702 (US Feet)
Terrain: 1-meter LIDAR (FEMA Region III 3DEP collected 2016-2018)
Land Use: 2019 NLCD
Hydrologic Method:
WV SIR2010-5033 regression equations
Additional Model Notes:
None
END DESCRIPTION:
DSS Export Rating Curves= 0
DSS Export Rating Curve Sorted= 0
DSS Export Volume Flow Curves= 0
DXF OffsetX= 0
DXF OffsetY= 0
DXF ScaleX= 0
DXF ScaleY= 0

--- BCKLERN.p01 (plan) ---

Plan Title=Floodplain
Program Version=6.20
Short Identifier=Floodplain
Geom File=g01
Flow File=f01
Subcritical Flow
K Sum by GR= 0
Std Step Tol= 0.01
Critical Tol= 0.01
Num of Std Step Trials= 20
Max Error Tol= 0.3
Flow Tol Ratio= 0.001
Split Flow NTrial= 30
Split Flow Tol= 0.02
Split Flow Ratio= 0.02
Log Output Level= 0
Friction Slope Method= 1
Unsteady Friction Slope Method= 2
Unsteady Bridges Friction Slope Method= 1
Parabolic Critical Depth
Global Vel Dist= 0 , 0 , 0
Global Log Level= 0
CheckData=True
Encroach Param=-1 ,0,0, 0
Mapping Interval=1HOUR
Computation Time Step Use Courant=        0
Computation Time Step Use Time Series=    0
Computation Time Step Count To Double=0
Computation Time Step Max Doubling=0
Computation Time Step Max Halving=0
Computation Time Step Residence Courant=0
Run HTab= 0
Run UNet= 0
Run Sediment= 0
Run PostProcess= 0
Run WQNet= 0
Run RASMapper=-1
UNET Theta= 0
UNET Theta Warmup= 0
UNET ZTol= 0
UNET ZSATol= 0
UNET MxIter= 0
UNET Max Iter WO Improvement= 0
UNET MaxInSteps= 0
UNET DtIC= 0
UNET DtMin= 0
UNET MaxCRTS= 0
UNET WFStab= 0
UNET SFStab= 0
UNET WFX= 1
UNET SFX= 1
UNET Gravity=32.174
UNET 1D Methodology=Finite Difference
UNET DSS MLevel= 1
UNET Pardiso=0
UNET DZMax Abort= 0
UNET Use Existing IB Tables= 0
UNET Froude Reduction=False
UNET Froude Limit= 0
UNET Froude Power= 0
UNET D1 Cores= 0
UNET WindReference=Eulerian
UNET WindDragFormulation=Hsu (1988)
UNET D2 Coriolis=0
UNET D2 Cores= 0
UNET D2 Theta= 1
UNET D2 Theta Warmup= 1
UNET D2 Z Tol= 0.01
UNET D2 Volume Tol= 0.01
UNET D2 Max Iterations= 20
UNET D2 Equation= 0
UNET D2 RampUpFraction=0.1
UNET D2 TimeSlices= 1
UNET D2 Turbulence Formulation=Non-Conservative (original)
UNET D2 Eddy Viscosity=0.3
UNET D2 Transverse Eddy Viscosity=0.1
UNET D2 Smagorinsky Mixing=0
UNET D2 BCVolumeCheck=0
UNET D2 Cores=0
UNET D2 SolverType=PARDISO (Direct)
UNET D2 Minimum Iterations= 2147483647
UNET D2 Maximum Iterations= 2147483647
UNET D2 Restart Number= 10
UNET D2 Relaxation Coeff=1.3
UNET D2 SOR Precondition Iterations= 10
UNET D2 ILUT Maximum Fill= 8
UNET D2 ILUT Tolerance=1E-08
UNET D1D2 MaxIter= 0
UNET D1D2 ZTol=0.01
UNET D1D2 QTol=0.1
UNET D1D2 MinQTol=1
Write IC File= 0
Write IC File at Fixed DateTime=0
Write IC File at Sim End=0
Echo Input=False
Echo Parameters=False
Echo Output=False
Write Detailed= 0
HDF Write Warmup=0
HDF Write Time Slices=0
HDF Flush=0
HDF Compression= 1
HDF Chunk Size= 1
HDF Spatial Parts= 1
HDF Use Max Rows=0
HDF Fixed Rows= 1
Calibration Method= 0
Calibration Iterations= 20
Calibration Max Change=0.05
Calibration Tolerance=0.2
Calibration Maximum=1.5
Calibration Minimum=0.5
Calibration Optimization Method= 1
WQ AD Non Conservative
WQ ULTIMATE=-1
WQ Max Comp Step=1HOUR
WQ Output Interval=15MIN
WQ Output Selected Increments= 0
WQ Output face flow=0
WQ Output face velocity=0
WQ Output face area=0
WQ Output face dispersion=0
WQ Output cell volume=0
WQ Output cell surface area=0
WQ Output cell continuity=0
WQ Output cumulative cell continuity=0
WQ Output face conc=0
WQ Output face dconc_dx=0
WQ Output face courant=0
WQ Output face peclet=0
WQ Output face adv mass=0
WQ Output face disp mass=0
WQ Output cell mass=0
WQ Output cell source sink temp=0
WQ Output nsm pathways=0
WQ Output nsm derived pathways=0
WQ Create Restart=0
WQ Fixed Restart=0
WQ System Summary=0
WQ Write To DSS=0
Sorting and Armoring Iterations= 10
XS Update Threshold= 0.02
Bed Roughness Predictor= 0
Hydraulics Update Threshold= 0.02
Energy Slope Method= 1
Volume Change Method= 1
Sediment Retention Method= 0
Sediment TS Multiplier= 1
Warm Up Method= 0
XS Weighting Method= 0
Number of US Weighted Cross Sections= 1
Number of DS Weighted Cross Sections= 1
Upstream XS Weight=0
Main XS Weight=1
Downstream XS Weight=0
Number of DS XS's Weighted with US Boundary= 1
Upstream Boundary Weight= 1
Weight of XSs Associated with US Boundary= 0
Number of US XS's Weighted with DS Boundary= 1
Downstream Boundary Weight= 0.5
Weight of XSs Associated with DS Boundary= 0.5
Percentile Method= 0
Sediment Output Level= 3
Mass or Volume Output= 0
Output Increment Type= 1
Profile and TS Output Increment= 1
Transport Output Increment 1
XS Output Flag= 0
XS Output Increment= 10
Read HDF5 Sediment Hotstart= 0
Sediment Hotstart Type= 0
Write Gradation File= 0
Read Gradation Hotstart= 0
Write HDF5 File= 1
Write Binary Output= 1
Write DSS Sediment File= 0
DSS Sediment Output Type= 1
SV Curve= 0
Specific Gage Flag= 0
Subcell Erosion Methods= 0
Subcell Deposition Methods= 0
Advection Scheme= 1
Matrix Solver= 0
Implicit Weighting Factor= 1
Maximum Outer Loop Convergence Iterations= 5
Convergence Maximum Absolute= 0.001
Convergence RMSE= 0.0001
Grain Fractions Max Abs Error= 0.001
Max Subgrid Regions= 1
Max Subgrid Length Scale= 3.402823E+38
Initial Layer Thickness= 3.402823E+38
Min Layer Thickness= 3.402823E+38
Max Layer Thickness= 3.402823E+38
Number of Layers= 5

--- BCKLERN.f01 (steady flow) ---

Flow Title=Flow
Program Version=6.20
Number of Profiles= 1
Profile Names=P100yr
River Rch & RM=BCKLERN,Main            ,5288
     371
River Rch & RM=BCKLERN,Main            ,4021
     413
River Rch & RM=BCKLERN,Main            ,3115
     468
Boundary for River Rch & Prof#=BCKLERN,Main            , 1
Up Type= 0
Dn Type= 3
Dn Slope=0.04379
DSS Import GetInterval= 0
DSS Import GetPeak= 0
DSS Import FillOption= 0

--- BCKLERN.g01 (geometry) ---

Geom Title=Geometry
Program Version=6.20

River Reach=BCKLERN         ,Main
Reach XY= 30
2334286.66296653702700.422949795     2334312.161      702617.699
     2334289.405      702432.255     2334417.293      702025.882
     2334299.932      701757.479     2334299.585      701688.729
2334386.65449723701465.184460314     2334449.932      701420.326
2334601.16006025701207.126286168     2334648.283      701087.427
2334820.06507531701039.405015061     2334921.286      700648.191
     2334870.071       700503.66 2334937.3625658700426.004131605
     2334987.692      700286.212     2335081.443      700208.521
2335163.44061191699905.809782901     2335161.521      699776.374
     2335093.812      699630.1932335081.71270333 699471.80629667
     2335111.694      699338.657     2335087.714      699193.391
     2335139.363      698858.105     2335098.565      698785.839
     2334993.906      698736.302     2334969.254      698521.719
     2334995.643      698417.552 2335106.2716892      698281.311
 2335143.7877558698184.367844601     2335268.891      698108.095

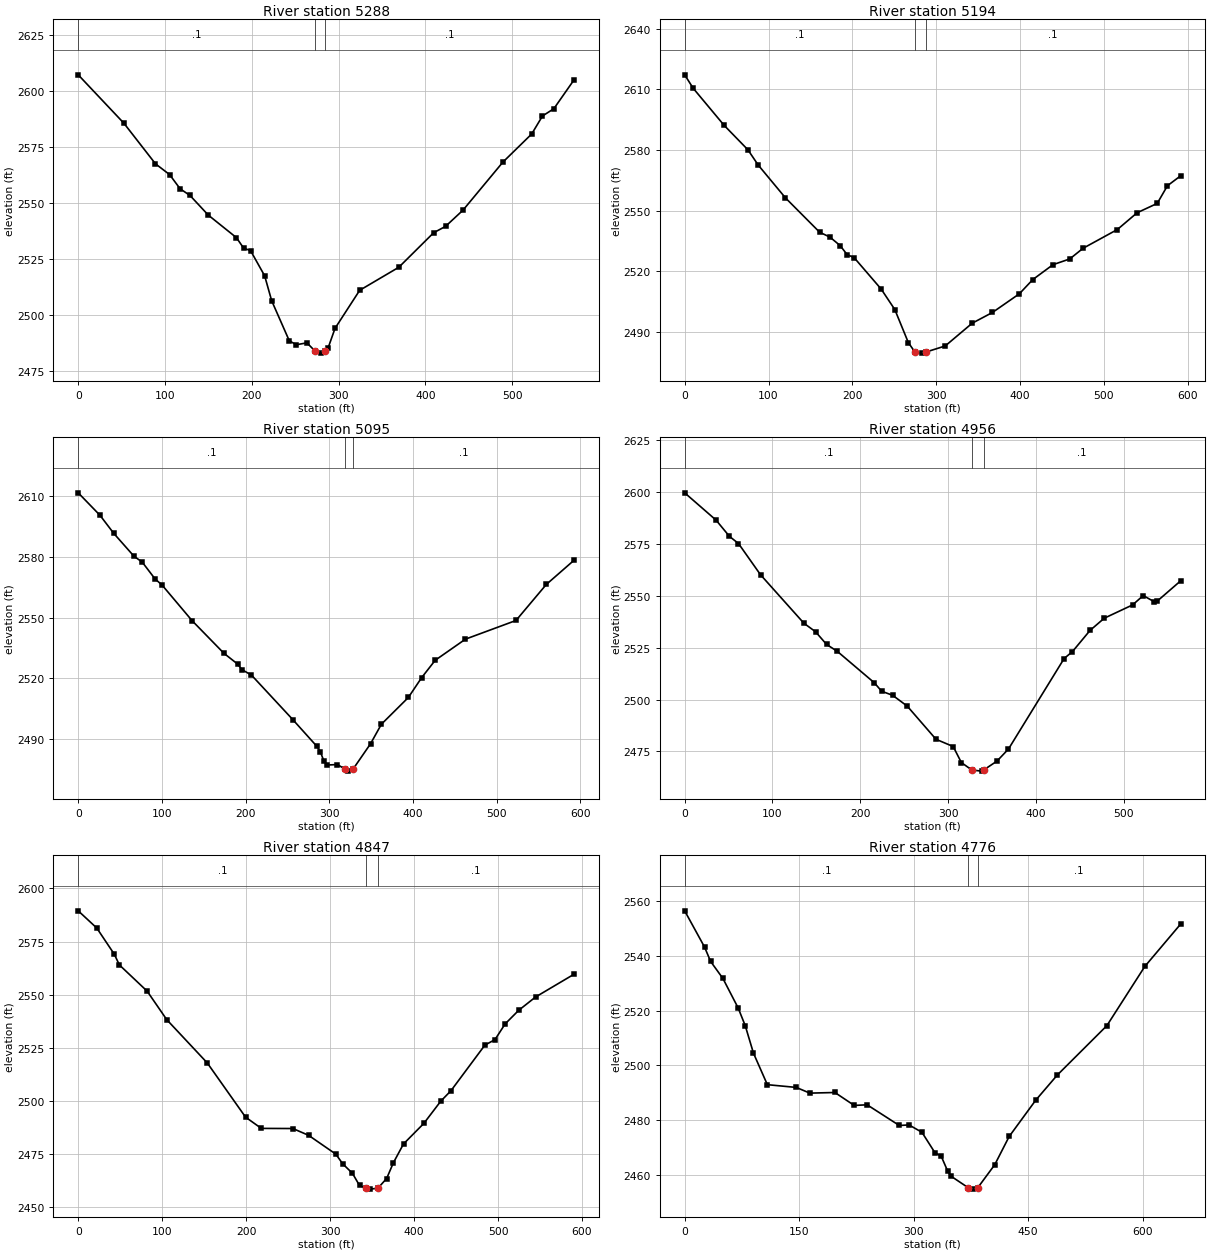
Type RM Length L Ch R = 1 ,5288    ,96.3,93.8,93.2
XS GIS Cut Line= 3
2334559.96623606702737.8092485682334220.62807936702680.478252768
2334000.91935693702738.508612828
#Sta/Elev= 30
       0 2607.31    52.7 2585.68      89  2567.6   105.3 2562.77   117.4 2556.45
   128.8 2553.46   149.9 2544.69   182.3 2534.63   190.5    2530   198.6 2528.82
   214.8 2517.61   222.9 2506.47   243.2 2488.59   251.3 2486.83   263.5 2487.68
  273.242483.881   279.7 2483.09   284.9 2483.91   287.8 2485.27   295.9 2494.16
   324.3 2511.13   369.4 2521.42   409.5 2536.82   423.2 2539.66   443.3 2546.89
   489.4 2568.39   522.5 2580.91   534.9 2588.94     548 2592.18   571.4 2605.15
#Mann= 3 ,-1,0
       0      .1       0  273.24    .045       0   284.9      .1       0
Bank Sta=273.24,284.9
XS Rating Curve= 0 ,0
Exp/Cntr(USF)=0,0
Exp/Cntr=0.3,0.1

Type RM Length L Ch R = 1 ,5194    ,99.6,99,98.8
XS GIS Cut Line= 3
 2334590.1643309702648.410153967 2334345.0913444702600.466153811
2334004.43162311702626.234012297
#Sta/Elev= 30
       0 2617.19    10.2 2610.51    46.9 2592.24    75.4 2580.07    87.6 2572.55
   120.2 2556.24     161 2539.22   173.2 2536.84   185.4 2532.62   193.6 2528.21
   202.2 2526.59   234.3  2511.1   250.6 2500.94   266.7 2484.59   274.7 2479.82
   282.7 2479.37287.24522479.845   310.7 2482.92   342.9  2494.2     367  2499.5
   399.1 2508.75   415.1 2515.79   439.2 2523.17   459.2 2526.01     475 2531.27
     516 2540.59   539.5 2548.88   563.5 2553.51   575.7 2562.27   591.4 2567.17
#Mann= 3 ,-1,0
       0      .1       0   274.7    .045       0287.2452      .1       0
Bank Sta=274.7,287.2452
XS Rating Curve= 0 ,0
Exp/Cntr(USF)=0,0
Exp/Cntr=0.3,0.1

Type RM Length L Ch R = 1 ,5095    ,137.2,139.7,145.1
XS GIS Cut Line= 4
2334609.45131935702576.3386310482334310.09823611702503.861865008
2334256.18027575702510.8534557722334027.04024136702486.599897988
#Sta/Elev= 30
       0 2611.63      26 2600.55    42.5 2591.61    66.6 2580.35    76.6 2577.38
    91.9 2569.09   100.1 2566.16   136.2 2548.47   174.2 2532.39   190.6 2527.06
   195.8  2524.3   207.1 2521.63   256.5 2499.66   285.3 2486.44   289.4 2483.78
   293.5 2479.38   297.6 2477.24   309.9 2477.46  318.34 2475.36     322 2474.22
   328.82475.377   349.4 2487.72   362.4 2497.38   394.6 2510.58   410.6 2520.43
   426.7 2528.95   462.9 2539.39   523.3 2548.61   559.5 2566.38   592.8 2578.39
#Mann= 3 ,-1,0
       0      .1       0  318.34    .045       0   328.8      .1       0
Bank Sta=318.34,328.8
XS Rating Curve= 0 ,0
Exp/Cntr(USF)=0,0
Exp/Cntr=0.3,0.1

Type RM Length L Ch R = 1 ,4956    ,110,108.1,104.5
XS GIS Cut Line= 4
2334630.82344001702480.0301644152334358.62227936702397.217641995
2334297.41302365702361.2121974642334090.02166316702331.687732949
#Sta/Elev= 30
       0 2599.74    35.8 2586.55      51 2578.73    61.3 2575.29    86.4 2560.22
   135.8 2536.84   149.1 2532.71   161.6 2526.63     174 2523.22     216 2508.12
   224.4 2504.02   236.9 2502.07   253.6 2496.82   286.3 2480.85   305.9 2477.35
   315.2 2469.62   327.2 2466.01   338.4 2465.48  340.51 2465.99   355.8 2470.32
   368.9 2476.15   432.3 2519.81   441.8 2523.16   461.8 2533.36     478 2539.25
   510.3 2545.67   522.4 2550.18   534.6 2547.27   538.6 2547.58     565 2557.27
#Mann= 3 ,-1,0
       0      .1       0   327.2    .045       0  340.51      .1       0
Bank Sta=327.2,340.51
XS Rating Curve= 0 ,0
Exp/Cntr(USF)=0,0
Exp/Cntr=0.3,0.1

Type RM Length L Ch R = 1 ,4847    ,70.6,71.7,73.3
XS GIS Cut Line= 4
2334628.66311334702453.3861354622334609.22017329702409.459493135
2334390.30707054702275.5192394822334106.58416764702240.233903842
#Sta/Elev= 30
       0 2589.47    22.1 2581.36      43 2568.99      49 2563.97    82.1 2551.59
   105.5 2538.13   153.7 2517.75   199.3 2492.19   218.1 2486.89   255.6 2486.83
   274.3 2483.64   306.8 2474.75   314.9 2470.23   326.6  2465.7     335 2459.98
   343.1 2458.63   347.1 2458.26   356.82458.658   367.3 2463.27   375.3 2470.67
   387.4 2479.57   411.6 2489.25   431.8 2499.74   443.9 2504.66   484.3 2526.16
   496.3 2528.74   508.4 2536.15   524.5 2542.54   544.6 2548.83   590.6 2559.61
#Mann= 3 ,-1,0
       0      .1       0   343.1    .045       0   356.8      .1       0
Bank Sta=343.1,356.8
XS Rating Curve= 0 ,0
Exp/Cntr(USF)=0,0
Exp/Cntr=0.3,0.1

Type RM Length L Ch R = 1 ,4776    ,129.8,128.4,127.1
XS GIS Cut Line= 4
 2334625.3372129702395.1709240042334620.02180665702287.040981731
2334226.12224348702153.8208369682334108.42052538702197.680006895
#Sta/Elev= 30
       0 2556.47      26 2543.23      34 2537.95    50.1 2531.72    70.1 2520.91
    79.4  2514.4    90.1 2504.41   108.3 2492.87   146.1 2491.87     164 2489.78
   196.8 2490.01   222.1 2485.28     239 2485.51   281.2 2477.94   293.9 2478.15
   310.8 2475.46   327.7 2468.05   336.1 2466.68   344.6 2461.21   349.4  2459.3
  371.172455.231   377.8 2454.66   384.1 2455.23   406.2 2463.59   425.1 2473.92
   459.9  2487.2   488.1 2496.38   553.1 2514.47   602.8 2536.12   649.7 2551.62
#Mann= 3 ,-1,0
       0      .1       0  371.17    .045       0   384.1      .1       0
Bank Sta=371.17,384.1
XS Rating Curve= 0 ,0
Exp/Cntr(USF)=0,0
Exp/Cntr=0.3,0.1

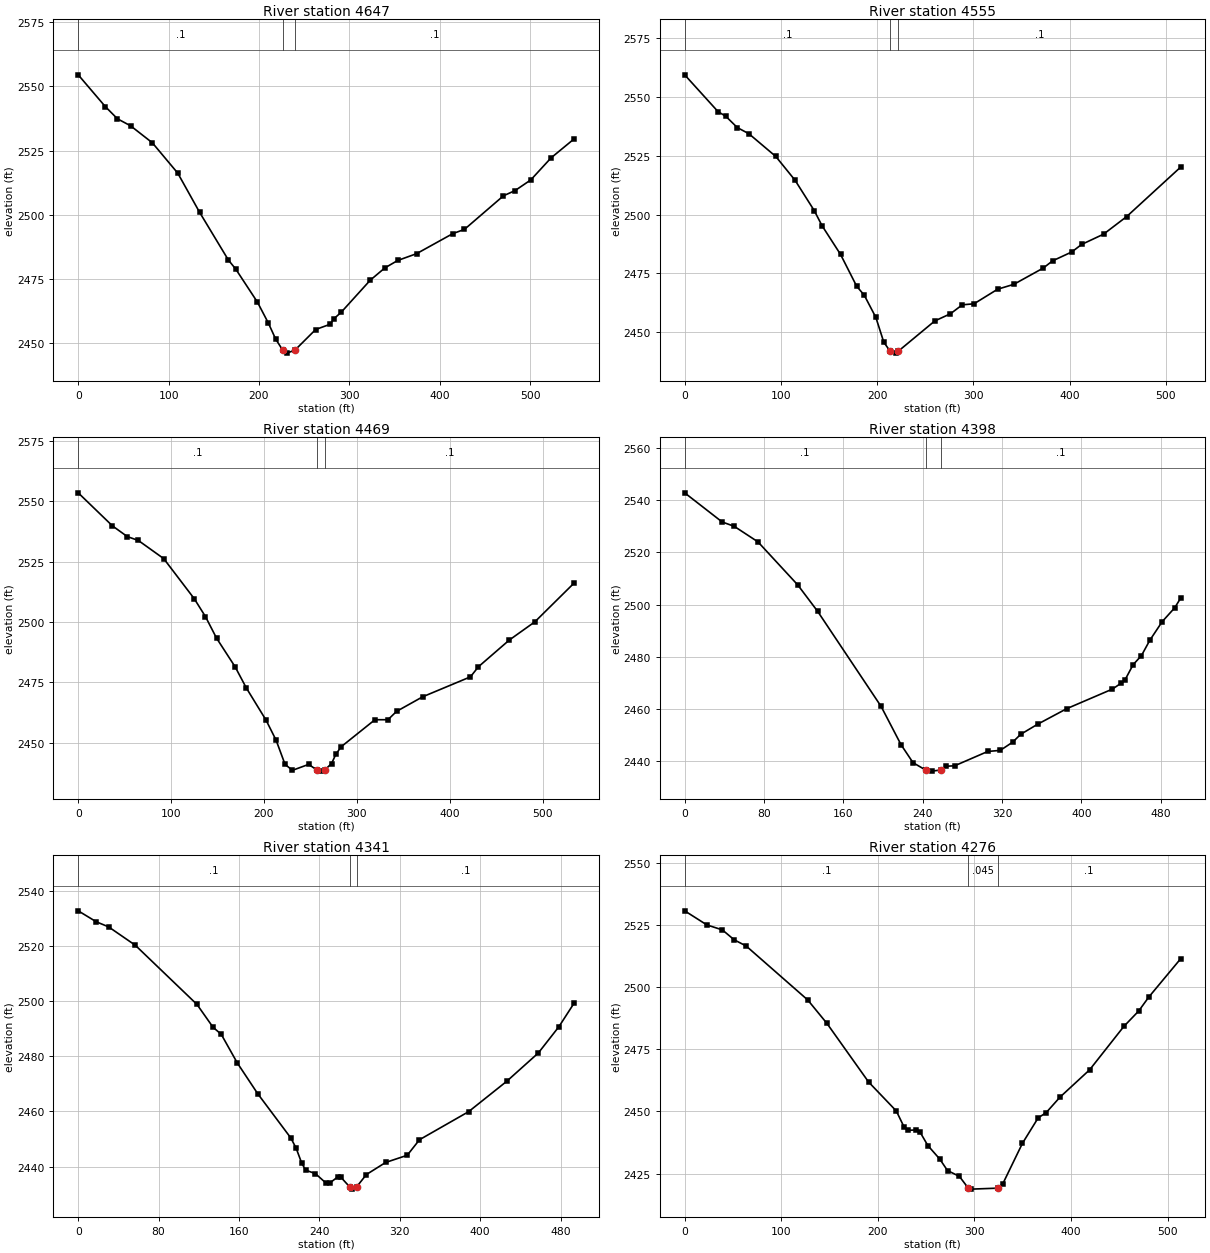
Type RM Length L Ch R = 1 ,4647    ,94.3,92.8,91.2
XS GIS Cut Line= 4
2334642.01057232702068.6560517592334428.43445497702083.516934379
2334269.32877692702064.5273345332334107.66835417702129.807442429
#Sta/Elev= 30
       0 2554.52    29.9 2542.19    43.4 2537.41      58 2534.67      82 2528.08
   110.1 2516.28   134.2 2501.08   166.2 2482.42   174.3 2478.92   198.3 2466.06
   210.3 2457.97   218.4 2451.73   226.4  2447.3   230.5 2446.22  239.592447.315
   262.7 2455.41   278.8 2457.46   282.8 2459.57   290.9  2462.1   323.1  2474.6
   339.2 2479.37   353.5 2482.28   374.3 2484.91   414.4 2492.72   427.3 2494.37
   470.5 2507.45   483.3 2509.47   500.7 2513.62   523.2 2522.22   548.7  2529.6
#Mann= 3 ,-1,0
       0      .1       0   226.4    .045       0  239.59      .1       0
Bank Sta=226.4,239.59
XS Rating Curve= 0 ,0
Exp/Cntr(USF)=0,0
Exp/Cntr=0.3,0.1

Type RM Length L Ch R = 1 ,4555    ,86.8,85.6,83.8
XS GIS Cut Line= 3
2334630.82297692701980.2997802172334433.35574414701985.402291837
2334121.65869882702047.727411308
#Sta/Elev= 30
       0 2559.26    34.7 2543.63    42.7 2541.69    54.7 2536.88    66.7 2534.28
    94.7 2524.62   114.7 2514.54   134.7 2501.63   142.7 2495.29     162 2483.06
   178.7 2469.61   186.7 2465.72   198.7 2456.33   206.9 2445.86  213.362442.092
   219.1  2441.2   222.1 2442.06   259.9 2454.85   276.2  2457.9   288.5 2461.69
   300.7 2462.13   325.2 2468.31   342.1 2470.39   372.7  2477.3   382.3 2480.34
   402.3 2484.12   412.5  2487.3   435.3 2491.66   459.4 2499.15   515.4  2520.1
#Mann= 3 ,-1,0
       0      .1       0  213.36    .045       0   222.1      .1       0
Bank Sta=213.36,222.1
XS Rating Curve= 0 ,0
Exp/Cntr(USF)=0,0
Exp/Cntr=0.3,0.1

Type RM Length L Ch R = 1 ,4469    ,70.8,71.2,71.5
XS GIS Cut Line= 4
2334625.06256888701903.9430519272334406.14946614701895.301745239
2334228.28257016 702002.597969942334122.42656324702019.160474424
#Sta/Elev= 30
       0 2553.54    36.9 2539.83    52.9  2535.4    64.7 2533.81    92.1 2526.27
     125 2509.64     137 2502.26     149  2493.3     169 2481.42     181  2472.7
   202.3 2459.32   213.1 2451.02   222.7 2441.03   230.7 2438.57   248.1 2441.02
   256.9 2438.75   261.4 2438.23   265.6 2438.77   272.8 2441.38   277.4  2445.2
   283.1 2448.32   319.5 2459.53   333.5 2459.53   342.8 2462.99   370.9 2469.03
   422.3 2477.29     431  2481.5   464.2 2492.55   491.7 2500.09     534 2516.18
#Mann= 3 ,-1,0
       0      .1       0   256.9    .045       0   265.6      .1       0
Bank Sta=256.9,265.6
XS Rating Curve= 0 ,0
Exp/Cntr(USF)=0,0
Exp/Cntr=0.3,0.1

Type RM Length L Ch R = 1 ,4398    ,60,56.5,54.9
XS GIS Cut Line= 3
2334609.94028218701854.2555384752334383.10598164701840.573469553
2334122.42656324701921.225665301
#Sta/Elev= 30
       0 2542.84    37.8 2531.67    49.9 2530.02    73.9 2524.05     114 2507.56
     134 2497.47   198.1 2460.99   218.2 2446.32   230.3 2439.43   242.9 2436.66
   242.9 2436.65     249 2436.21   258.9 2436.66   263.8 2438.09   272.2 2438.25
   305.7 2443.76   318.2 2444.15   330.8 2447.33   338.8 2450.31   355.9 2454.18
   385.2 2460.13   431.3 2467.64   439.7  2469.8   443.9 2471.08   452.2 2476.99
   460.6 2480.48     469 2486.32   481.5 2493.47   494.1 2498.78   500.1 2502.47
#Mann= 3 ,-1,0
       0      .1       0   242.9    .045       0   258.9      .1       0
Bank Sta=242.9,258.9
XS Rating Curve= 0 ,0
Exp/Cntr(USF)=0,0
Exp/Cntr=0.3,0.1

Type RM Length L Ch R = 1 ,4341    ,60.7,64.9,67.6
XS GIS Cut Line= 4
 2334598.3012305 701805.017511842334338.60324323701793.873250002
2334294.31772015701822.9795809892334117.26849157701858.305569745
#Sta/Elev= 30
       0 2532.78    18.1 2528.78    30.2 2526.97    56.8  2520.3   118.2 2498.82
   134.2 2490.53   142.3 2488.01   158.3 2477.61   178.5 2466.51   211.6 2450.38
   216.9 2446.65   222.3 2441.36   226.3 2438.74   236.1 2437.44   246.4 2434.09
   250.4 2434.08   258.4 2436.31   261.2 2436.21  269.98 2432.72   272.4 2431.84
   277.2 2432.74   286.8 2437.14   305.9 2441.51   327.4 2444.12   339.6 2449.76
   388.5 2459.94   426.4 2470.95   457.9 2481.24   478.3 2490.74   493.5 2499.33
#Mann= 3 ,-1,0
       0      .1       0  269.98    .045       0   277.2      .1       0
Bank Sta=269.98,277.2
XS Rating Curve= 0 ,0
Exp/Cntr(USF)=0,0
Exp/Cntr=0.3,0.1

Type RM Length L Ch R = 1 ,4276    ,77.1,84.9,88.6
XS GIS Cut Line= 3
2334606.33973773701774.3234516172334385.26630831701726.796264837
2334103.70373208701783.684867195
#Sta/Elev= 30
       0  2530.6      23 2524.93      39 2522.94    51.3 2518.94    63.6 2516.48
   127.4 2494.77   147.3 2485.34   190.4  2461.8   219.1 2450.15   227.2 2443.65
   231.3 2442.39   239.5 2442.52   243.6 2441.71   251.7 2436.28     264 2430.86
   272.1 2426.21   284.4 2423.87   293.6 2419.14   296.6 2418.75   324.1 2419.14
   329.3 2420.88   349.7  2437.2     366 2447.43   374.1 2449.44   388.6 2455.75
   419.2  2466.7   454.6 2484.13     470 2490.34   480.5 2495.97   513.4 2511.32
#Mann= 3 ,-1,0
       0      .1       0   293.6    .045       0   324.1      .1       0
Bank Sta=293.6,324.1
XS Rating Curve= 0 ,0
Exp/Cntr(USF)=0,0
Exp/Cntr=0.3,0.1

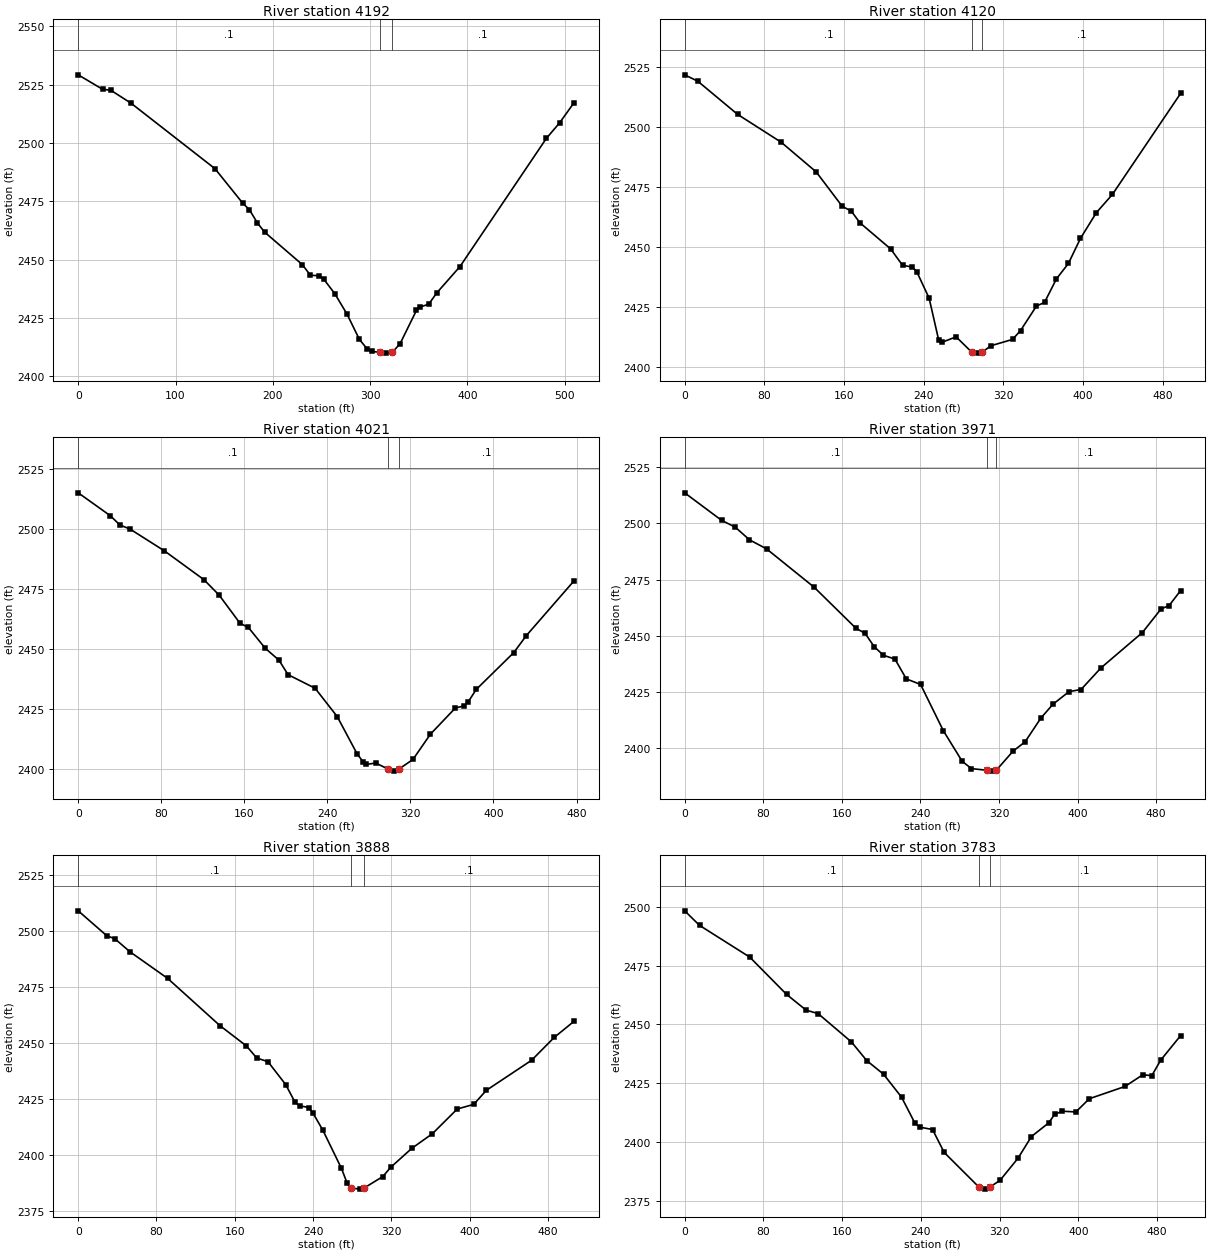
Type RM Length L Ch R = 1 ,4192    ,70.6,71.1,72.1
XS GIS Cut Line= 3
2334612.10060885701757.0408382422334249.88583687701644.703851307
2334119.54612767701642.543524635
#Sta/Elev= 30
       0 2529.18      25 2522.99    33.4 2522.59    54.4 2516.98   140.5 2488.95
   169.2 2474.08   175.8 2471.43   184.2 2465.63   191.6 2461.72   230.3 2447.81
   238.6 2443.26     247 2443.06   252.4 2441.53   263.8 2435.26   276.3 2426.53
   288.9 2415.77   296.6 2411.82   301.5 2410.63   310.1 2410.21   316.3 2409.87
   322.7 2410.16   330.8 2413.97   347.5 2428.15   351.7 2429.71   360.1 2430.83
   368.5 2435.73   392.3    2447     481 2501.91   494.6 2508.57   509.6 2517.31
#Mann= 3 ,-1,0
       0      .1       0   310.1    .045       0   322.7      .1       0
Bank Sta=310.1,322.7
XS Rating Curve= 0 ,0
Exp/Cntr(USF)=0,0
Exp/Cntr=0.3,0.1

Type RM Length L Ch R = 1 ,4120    ,98.5,99.1,98.6
XS GIS Cut Line= 3
2334604.61147638701718.2269690392334308.35867879701584.430737164
 2334135.8205886701571.180733577
#Sta/Elev= 30
       0 2521.76    13.2 2519.09    53.1 2505.29      97 2493.64   132.1 2481.28
   158.3 2466.91   167.3 2464.98     176 2460.08   206.8 2449.21   218.8 2442.38
   228.7 2441.62   233.1 2439.69   245.5 2428.67   255.2 2411.03   258.1 2410.21
   272.6 2412.54   288.4 2406.13   294.1 2405.75   298.9 2406.22   307.7 2408.84
   329.3 2411.47   337.3 2415.14   353.3 2425.37   361.4 2426.89   373.4 2436.72
   385.4 2443.12   397.5 2453.57   413.5 2464.32   429.6 2471.91   498.1 2514.01
#Mann= 3 ,-1,0
       0      .1       0   288.4    .045       0   298.9      .1       0
Bank Sta=288.4,298.9
XS Rating Curve= 0 ,0
Exp/Cntr(USF)=0,0
Exp/Cntr=0.3,0.1

Type RM Length L Ch R = 1 ,4021    ,50,50.4,50.6
XS GIS Cut Line= 4
2334622.07360886701666.5871413232334395.23930832701520.765090971
2334341.44717419701493.5449749062334194.32892783701479.934916873
#Sta/Elev= 30
       0 2514.99    30.8  2505.5    40.3 2501.56    49.8 2499.94    83.1 2490.81
   121.1 2478.84   135.8 2472.39   155.8 2460.72   163.9 2458.96   180.1 2450.32
   193.4 2445.32   202.1 2439.31   228.2 2433.65   249.5 2421.85   268.6 2406.38
   274.6 2402.93   277.6 2401.97   286.6 2402.52   298.4 2400.04   304.4 2399.16
     309 2400.04   322.4 2404.01   339.3 2414.56   363.4 2425.49   371.4 2426.24
   375.4 2427.84   383.4 2433.16   419.5 2448.48   431.7 2455.59   477.7 2478.42
#Mann= 3 ,-1,0
       0      .1       0   298.4    .045       0     309      .1       0
Bank Sta=298.4,309
XS Rating Curve= 0 ,0
Exp/Cntr(USF)=0,0
Exp/Cntr=0.3,0.1

Type RM Length L Ch R = 1 ,3971    ,83.3,82.8,81.8
XS GIS Cut Line= 3
2334656.17127296701627.9973250452334372.44837006701451.570646845
2334204.66299855701419.165746768
#Sta/Elev= 30
       0 2513.63    37.7 2501.33    51.4 2498.37    65.9 2492.72    83.4 2488.65
   131.9 2471.54   174.3 2453.32   183.7 2451.01   193.1 2445.01   202.4 2441.25
   214.1 2439.55   225.7 2430.71   240.2 2428.26   263.4 2407.62   282.6 2393.99
     292 2390.75   308.3 2389.99   312.8 2389.63  317.292390.003   334.4 2398.55
   346.6 2402.67   362.9 2413.38   375.1 2419.47   391.4 2425.06   403.6    2426
     424 2435.67   466.1 2451.39   485.1 2461.91   493.3 2463.41     505 2470.07
#Mann= 3 ,-1,0
       0      .1       0   308.3    .045       0  317.29      .1       0
Bank Sta=308.3,317.29
XS Rating Curve= 0 ,0
Exp/Cntr(USF)=0,0
Exp/Cntr=0.3,0.1

Type RM Length L Ch R = 1 ,3888    ,105.9,105.5,104.5
XS GIS Cut Line= 4
2334681.23106235701584.9348133862334527.12775976 701458.91575753
2334434.23371287  701399.86682852334247.00540131701336.497246126
#Sta/Elev= 30
       0 2509.16      29  2498.1    37.5 2496.66      53 2490.83    91.5 2478.94
   144.9 2457.85   171.9  2448.8   182.5 2443.39   193.9 2441.78     212 2431.56
   221.5 2423.71   226.3 2422.05   235.7  2421.3   239.6 2419.03     250 2411.17
   268.9  2394.2   274.9 2387.44   278.4 2385.32   287.9 2384.84   291.8 2385.25
   311.3 2390.46   319.2 2394.53   340.9 2403.06     362 2409.62   387.3 2420.62
   404.2 2422.71     417 2428.95   463.3  2442.4   486.4 2452.59   506.8 2459.86
#Mann= 3 ,-1,0
       0      .1       0   278.4    .045       0   291.8      .1       0
Bank Sta=278.4,291.8
XS Rating Curve= 0 ,0
Exp/Cntr(USF)=0,0
Exp/Cntr=0.3,0.1

Type RM Length L Ch R = 1 ,3783    ,91,92.7,94.2
XS GIS Cut Line= 3
2334722.83735381701513.083948524 2334562.4130954701352.339641719
2334318.29618148701221.999932519
#Sta/Elev= 30
       0 2498.28    15.1 2492.09    66.1 2478.58   103.6 2462.68   123.4    2456
   135.5 2454.56   169.4 2442.48     185 2434.52     202 2428.76   220.3 2418.99
     234 2407.83   238.7 2406.24   251.8 2405.21   263.6 2395.47   299.1 2380.64
     305 2379.85  309.692380.633   320.3 2383.56   338.5 2392.94   352.3 2402.24
   369.7 2408.01   375.9  2411.7   383.8    2413   397.4  2412.7     411 2418.31
   447.3 2423.54   465.4 2428.53   474.5 2428.13   483.6 2434.76   503.8 2445.17
#Mann= 3 ,-1,0
       0      .1       0   299.1    .045       0  309.69      .1       0
Bank Sta=299.1,309.69
XS Rating Curve= 0 ,0
Exp/Cntr(USF)=0,0
Exp/Cntr=0.3,0.1

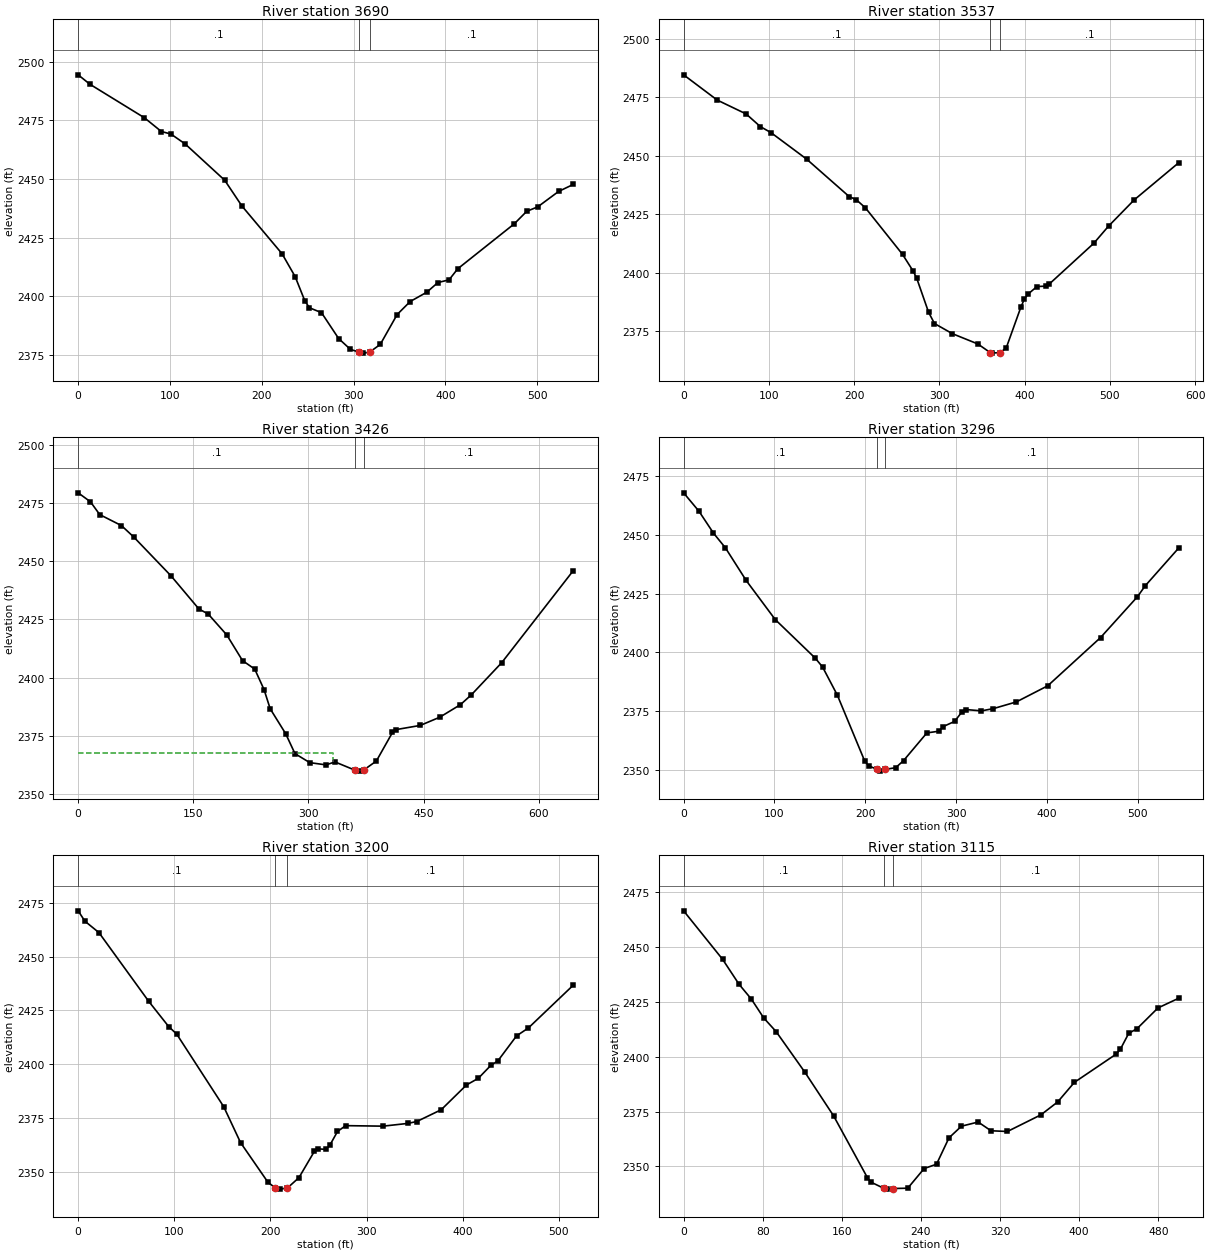
Type RM Length L Ch R = 1 ,3690    ,154.3,153.2,149.3
XS GIS Cut Line= 5
2334732.21089837701497.4150002482334705.80690571701419.803264261
2334594.59008816701286.1830590032334537.40363374701228.152090933
 2334353.7536703701144.561643849
#Sta/Elev= 30
       0  2494.4    12.8 2490.38    72.1  2476.1    90.6 2470.23     101 2469.16
   116.6  2464.9   159.6 2449.44   178.3 2438.48   222.1 2418.07   236.3 2408.36
   246.9 2397.97   251.9 2395.07     265 2392.98   283.7 2381.94   296.5 2377.33
   306.12376.124   310.6 2375.73   317.32376.124     329 2379.44   347.4  2392.2
   361.6 2397.74   379.7 2401.71   391.8 2405.84   403.9 2406.97   413.4  2411.7
   474.9 2430.85   488.5  2436.2   500.5  2438.1   523.2 2444.67   539.1 2447.65
#Mann= 3 ,-1,0
       0      .1       0   306.1    .045       0   317.3      .1       0
Bank Sta=306.1,317.3
XS Rating Curve= 0 ,0
Exp/Cntr(USF)=0,0
Exp/Cntr=0.3,0.1

Type RM Length L Ch R = 1 ,3537    ,104.9,110.5,121.1
XS GIS Cut Line= 3
2334746.84098349701455.4752372752334650.02634376701127.425631552
2334427.59270866701041.012564679
#Sta/Elev= 30
       0 2484.64    39.4 2473.85    73.3 2467.92      90 2462.51   102.5 2459.93
   144.2 2448.63   194.2  2432.6   202.6 2431.23   213.3 2427.76   256.8 2407.88
   269.3 2400.71   273.5 2397.62   287.4 2383.09   294.3 2378.31   315.2 2373.99
   345.2 2369.57  359.522365.926   361.2 2365.66  371.152365.904   378.4 2367.83
   395.5 2385.19   399.8 2388.87   404.1 2390.91   414.5 2394.13   425.6 2394.31
   428.6 2395.08   481.2 2412.63   498.5 2419.97   528.5 2431.15   580.7 2447.03
#Mann= 3 ,-1,0
       0      .1       0  359.52    .045       0  371.15      .1       0
Bank Sta=359.52,371.15
XS Rating Curve= 0 ,0
Exp/Cntr(USF)=0,0
Exp/Cntr=0.3,0.1

Type RM Length L Ch R = 1 ,3426    ,134.9,130.5,120.8
XS GIS Cut Line= 5
2334756.44243537701433.0718495672334710.36349263701090.974919439
2334718.49358576701056.0807021162334705.11035372701016.935313195
2334504.40432366700920.994416244
#Sta/Elev= 30
       0 2479.57      16 2475.71    28.1 2470.19    56.4 2465.45    72.5  2460.5
     121 2443.78   157.3 2429.52   169.4 2427.35   193.6 2418.33   214.1 2407.28
     230 2403.63   242.1 2394.82   250.1 2386.55   270.3 2375.79   282.4 2367.21
   301.7 2363.33   322.8 2362.36   334.5 2363.64   360.42360.102   367.6 2359.67
  371.74  2360.1   388.4 2364.01   409.4 2376.33   413.7 2377.54   445.6 2379.36
   470.9 2382.88   497.9  2388.3   512.1 2392.52   551.7 2406.39   644.8    2446
#Mann= 3 ,-1,0
       0      .1       0   360.4    .045       0  371.74      .1       0
#XS Ineff= 2 , 0
          332.52  2367.4
Permanent Ineff=
       F       F
Bank Sta=360.4,371.74
XS Rating Curve= 0 ,0
Exp/Cntr(USF)=0,0
Exp/Cntr=0.3,0.1

Type RM Length L Ch R = 1 ,3296    ,97.7,96.3,94.3
XS GIS Cut Line= 3
2335037.10996283701043.4731544872334872.28503898701045.873517456
 2334517.8314406 700908.25270725
#Sta/Elev= 30
       0 2467.75    16.9 2459.94    32.9 2450.63      46 2444.42    68.9 2430.55
   100.9 2413.97     145 2397.58     153 2393.85   169.3 2381.88   199.3 2354.03
   203.6 2351.98  213.05 2350.38   216.5 2349.66   221.62350.382   233.5 2351.11
   242.2 2354.13   267.9 2365.89   280.8 2366.58     286 2368.59   298.4 2370.76
   306.6 2374.86   310.4 2375.81     328 2375.23   340.9 2376.17   366.4 2379.03
     401 2385.88   459.1 2406.33   499.7 2423.65   508.2 2428.25   545.1  2444.3
#Mann= 3 ,-1,0
       0      .1       0  213.05    .045       0   221.6      .1       0
Bank Sta=213.05,221.6
XS Rating Curve= 0 ,0
Exp/Cntr(USF)=0,0
Exp/Cntr=0.3,0.1

Type RM Length L Ch R = 1 ,3200    ,83.6,84.7,86
XS GIS Cut Line= 4
2335058.88816943700989.0047003582334880.46118875700939.397199004
2334793.24800089700931.3959891092334569.21412381700839.382075309
#Sta/Elev= 30
       0 2471.24       7 2466.43    21.6 2461.13    73.4  2429.2    94.2 2417.46
   102.5 2413.99   151.5  2380.2   168.9 2363.61   197.5 2345.12   205.2 2342.52
   209.6 2341.97   217.6 2342.46   229.7 2347.31   245.7 2359.49   249.8 2360.67
   257.8 2360.43   261.8 2362.34   269.8 2368.75   278.3 2371.46   317.2 2371.22
   342.7 2372.48   352.3 2373.37   377.7 2378.85     404 2390.35   416.3 2393.45
   429.6 2399.58   436.5 2401.46   456.1 2413.16   468.4 2416.83     515 2436.67
#Mann= 3 ,-1,0
       0      .1       0   205.2    .045       0   217.6      .1       0
Bank Sta=205.2,217.6
XS Rating Curve= 0 ,0
Exp/Cntr(USF)=0,0
Exp/Cntr=0.3,0.1

Type RM Length L Ch R = 1 ,3115    ,103.5,103,102.5
XS GIS Cut Line= 3
2335078.09107318700912.9932063492334825.25284047700840.982317288
 2334600.4188424700764.170702289
#Sta/Elev= 30
       0  2466.6    39.4 2444.48    56.1 2433.05    68.5 2426.32      81 2417.72
    93.5 2411.51   122.6 2392.97   151.7    2373   185.9 2344.79   189.1 2342.88
  202.592339.953   205.8 2339.62   211.8  2339.9   226.6 2340.04   243.2 2349.02
   255.7 2350.98   268.3 2363.02   280.9 2368.34   297.8 2370.23   310.8 2366.25
   327.4 2365.92   361.3 2373.53   378.2  2379.4   395.1 2388.34   437.3 2401.21
   441.6 2403.45     450 2410.68   458.5 2412.86   479.6 2422.29   500.5  2426.7
#Mann= 3 ,-1,0
       0      .1       0  202.59    .045       0   211.8      .1       0
Bank Sta=202.59,211.8
XS Rating Curve= 0 ,0
Exp/Cntr(USF)=0,0
Exp/Cntr=0.3,0.1

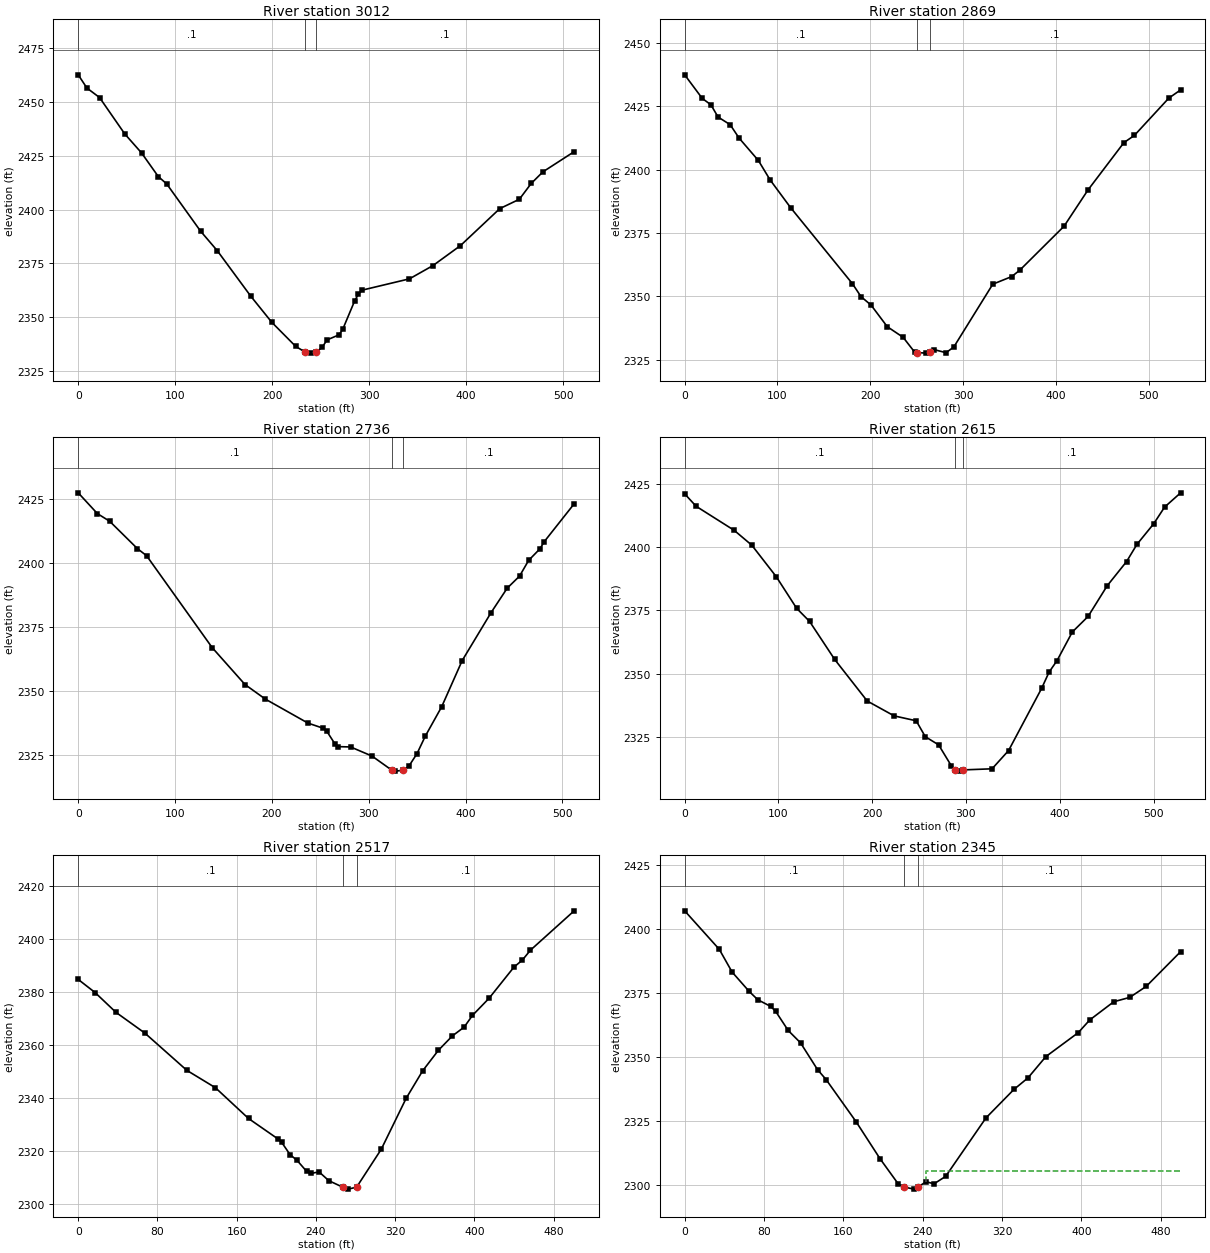
Type RM Length L Ch R = 1 ,3012    ,145,142.6,138.5
XS GIS Cut Line= 3
2335112.49627573700837.7818333292334923.66772219700759.369976352
2334620.42186714700712.162837968
#Sta/Elev= 30
       0 2462.62       9 2456.47      22 2452.07      48 2435.16    65.3 2426.33
    82.6 2415.33    91.3 2411.89   126.2 2389.95   143.3 2380.94   177.9 2359.76
   199.7 2347.56   224.2 2336.42     234 2333.76   240.4 2333.27  245.532333.804
   251.5 2335.93   256.6 2339.42     269 2341.78   272.8 2344.38   284.9 2357.38
     289 2360.77     293 2362.57   341.6  2367.8   365.9 2373.99   394.2 2383.26
   434.7 2400.43   454.9 2404.79   467.1 2412.12   479.2 2417.53   511.4  2426.9
#Mann= 3 ,-1,0
       0      .1       0     234    .045       0  245.53      .1       0
Bank Sta=234,245.53
XS Rating Curve= 0 ,0
Exp/Cntr(USF)=0,0
Exp/Cntr=0.3,0.1

Type RM Length L Ch R = 1 ,2869    ,129.1,133.4,136.4
XS GIS Cut Line= 4
2335157.30305114700696.9605391662334946.87123089700608.147109324
2334846.85610719700640.1519489062334647.62598079700613.747956251
#Sta/Elev= 30
       0  2437.5      19 2428.16    28.2  2425.7      36 2420.83      49 2417.82
    58.7 2412.49    79.4 2403.68      92 2396.05   114.1 2385.08   180.8 2355.01
     190 2349.93   200.9 2346.56   218.3 2338.06   235.4 2333.86     248 2327.92
  250.242327.856     260 2327.62  263.812327.885     269 2328.99   281.6 2327.79
     290 2330.04     332 2354.84   352.3 2357.83     361 2360.33   408.8 2377.73
   434.6 2392.05   473.3 2410.74   484.5 2413.55   521.7 2428.31   534.4 2431.55
#Mann= 3 ,-1,0
       0      .1       0  250.24    .045       0  263.81      .1       0
Bank Sta=250.24,263.81
XS Rating Curve= 0 ,0
Exp/Cntr(USF)=0,0
Exp/Cntr=0.3,0.1

Type RM Length L Ch R = 1 ,2736    ,118.7,120.7,122.1
XS GIS Cut Line= 2
2335182.90692281700608.1471093242334698.83372412700440.921822504
#Sta/Elev= 30
       0 2427.43    19.8 2419.31    32.5 2416.32    61.1 2405.64    70.6 2402.86
   138.3 2366.97   172.2 2352.54   193.2 2346.85   237.2 2337.47     253 2335.45
   256.8 2334.21   265.3 2329.21   268.7 2328.27   281.3 2328.14   303.4 2324.58
  323.822319.071   327.6  2318.7   335.8 2319.05   341.4 2320.62   349.9 2325.58
   358.4 2332.37   375.3 2343.84   396.5 2361.91   426.3 2380.63     443  2390.2
   455.7 2394.88   465.1 2401.04   476.9  2405.6   481.1  2408.3   512.1 2423.13
#Mann= 3 ,-1,0
       0      .1       0  323.82    .045       0   335.8      .1       0
Bank Sta=323.82,335.8
XS Rating Curve= 0 ,0
Exp/Cntr(USF)=0,0
Exp/Cntr=0.3,0.1

Type RM Length L Ch R = 1 ,2615    ,98.4,97.8,96.3
XS GIS Cut Line= 3
2335192.50837468700565.7406968772334896.46360854700376.912143339
2334724.43759579700332.105367923
#Sta/Elev= 30
       0 2420.98    12.2 2416.07    52.8 2406.57    71.6  2400.7    97.7 2388.25
   119.4 2375.78   133.2 2370.61     160 2355.58   194.7 2339.17   223.4  2333.3
   246.9 2331.37   256.6 2325.09   270.8 2321.87   284.5 2313.52   288.52311.983
   293.2 2311.49   297.22311.975   327.8 2312.41   345.4  2319.6   380.7 2344.19
   388.6 2350.58   397.1 2355.13   413.4 2366.43   430.2 2372.56   450.6 2384.69
   471.3 2394.26   482.3 2401.02   500.2 2409.17   511.8 2415.74   528.9 2421.38
#Mann= 3 ,-1,0
       0      .1       0   288.5    .045       0   297.2      .1       0
Bank Sta=288.5,297.2
XS Rating Curve= 0 ,0
Exp/Cntr(USF)=0,0
Exp/Cntr=0.3,0.1

Type RM Length L Ch R = 1 ,2517    ,169.4,172.6,165.9
XS GIS Cut Line= 2
2335236.51502911700396.9151680782334758.04267735700249.692905998
#Sta/Elev= 30
       0 2384.87    17.1 2379.89      38 2372.46    67.3 2364.58   109.7 2350.49
   138.5 2343.94   171.9 2332.31   201.7 2324.56   205.4 2323.27   213.8 2318.68
   220.9 2316.47   230.5 2312.36   234.7 2311.52   243.1 2312.13   252.9 2308.82
   266.9 2306.37   272.4 2305.61  281.012306.351   305.9 2320.69     331 2339.92
   347.7 2350.34   363.6  2358.1   377.7 2363.53   389.6 2366.86   397.9 2371.25
   414.7 2377.74   439.8 2389.51   448.3 2392.18   456.5 2395.93   500.6  2410.8
#Mann= 3 ,-1,0
       0      .1       0   266.9    .045       0  281.01      .1       0
Bank Sta=266.9,281.01
XS Rating Curve= 0 ,0
Exp/Cntr(USF)=0,0
Exp/Cntr=0.3,0.1

Type RM Length L Ch R = 1 ,2345    ,99.2,99.8,101.5
XS GIS Cut Line= 3
2335292.52349838700272.0962937062335101.29458187700195.284678707
2334809.25042068700161.679597146
#Sta/Elev= 30
       0 2407.25    34.9 2392.19    47.8 2383.32      65 2375.76    73.7 2372.49
    86.6  2369.9    91.7 2367.97   104.4 2360.46   116.8 2355.65     134 2345.14
   142.6 2341.28   172.8 2324.82   197.1 2310.26   215.3  2300.5  220.69 2299.28
   231.4 2298.43   235.4 2299.28   243.4 2301.32   251.5 2300.52   263.2 2303.43
   303.8 2326.27     332 2337.41   346.2 2341.94   364.2 2350.25   396.8 2359.59
   408.5 2364.59   432.7  2371.7   448.8  2373.4   465.4  2377.7   500.1 2391.28
#Mann= 3 ,-1,0
       0      .1       0  220.69    .045       0   235.4      .1       0
#XS Ineff= 2 , 0
                           243.7         2305.48
Permanent Ineff=
       F       F
Bank Sta=220.69,235.4
XS Rating Curve= 0 ,0
Exp/Cntr(USF)=0,0
Exp/Cntr=0.3,0.1