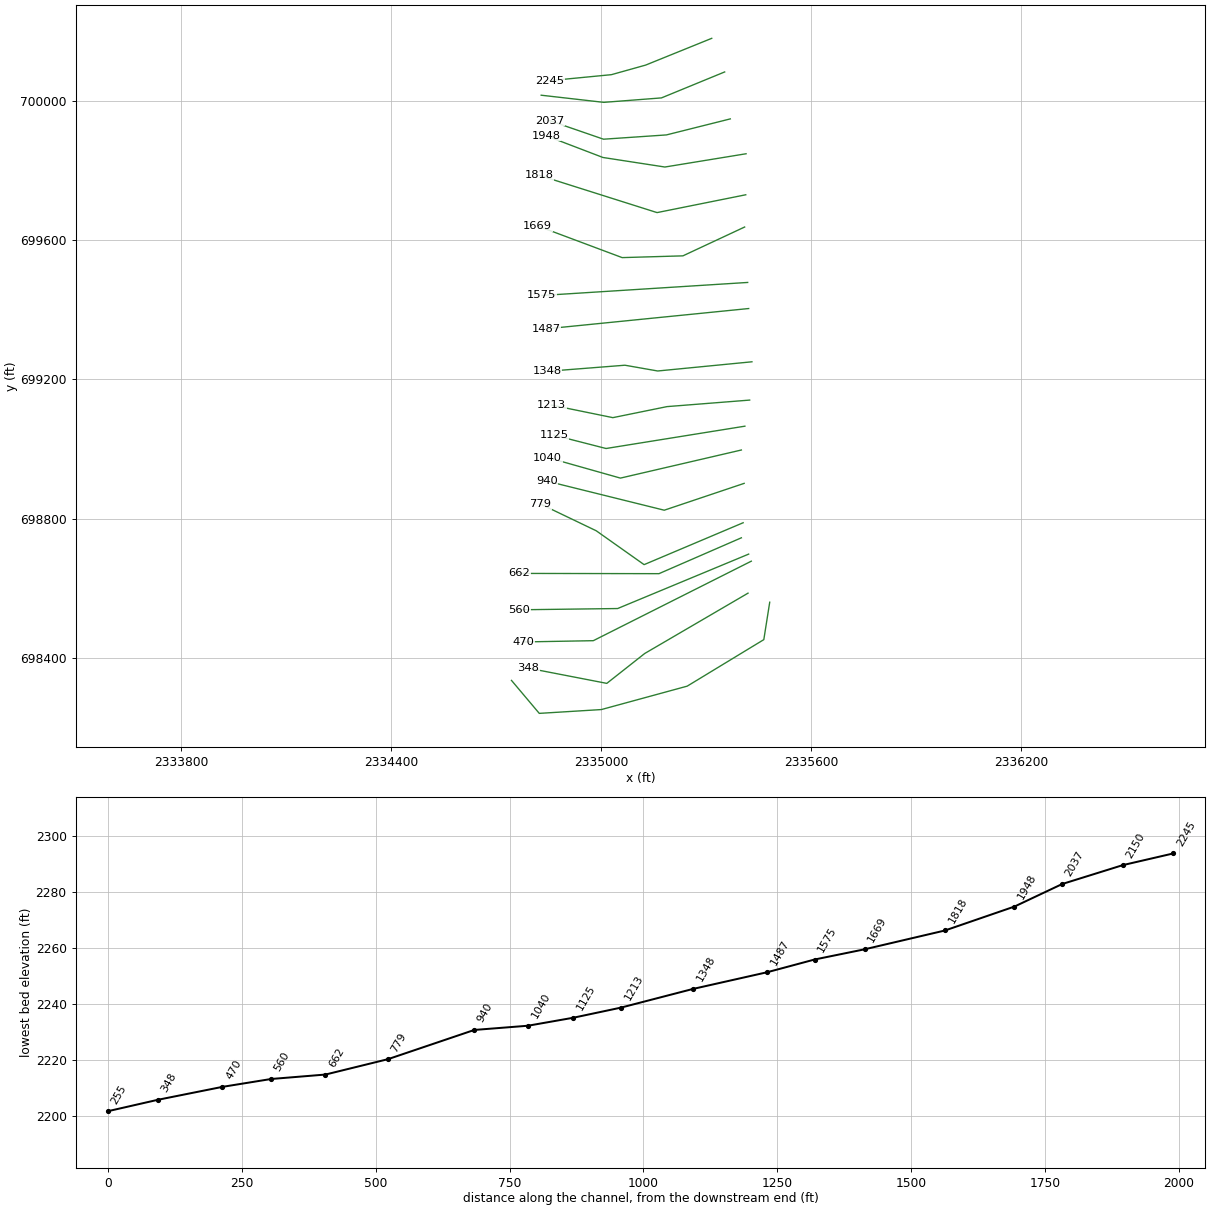
HEC-RAS study BCKLERN.prj: BCKLERN

--- BCKLERN.g01 (geometry) --- (continued)

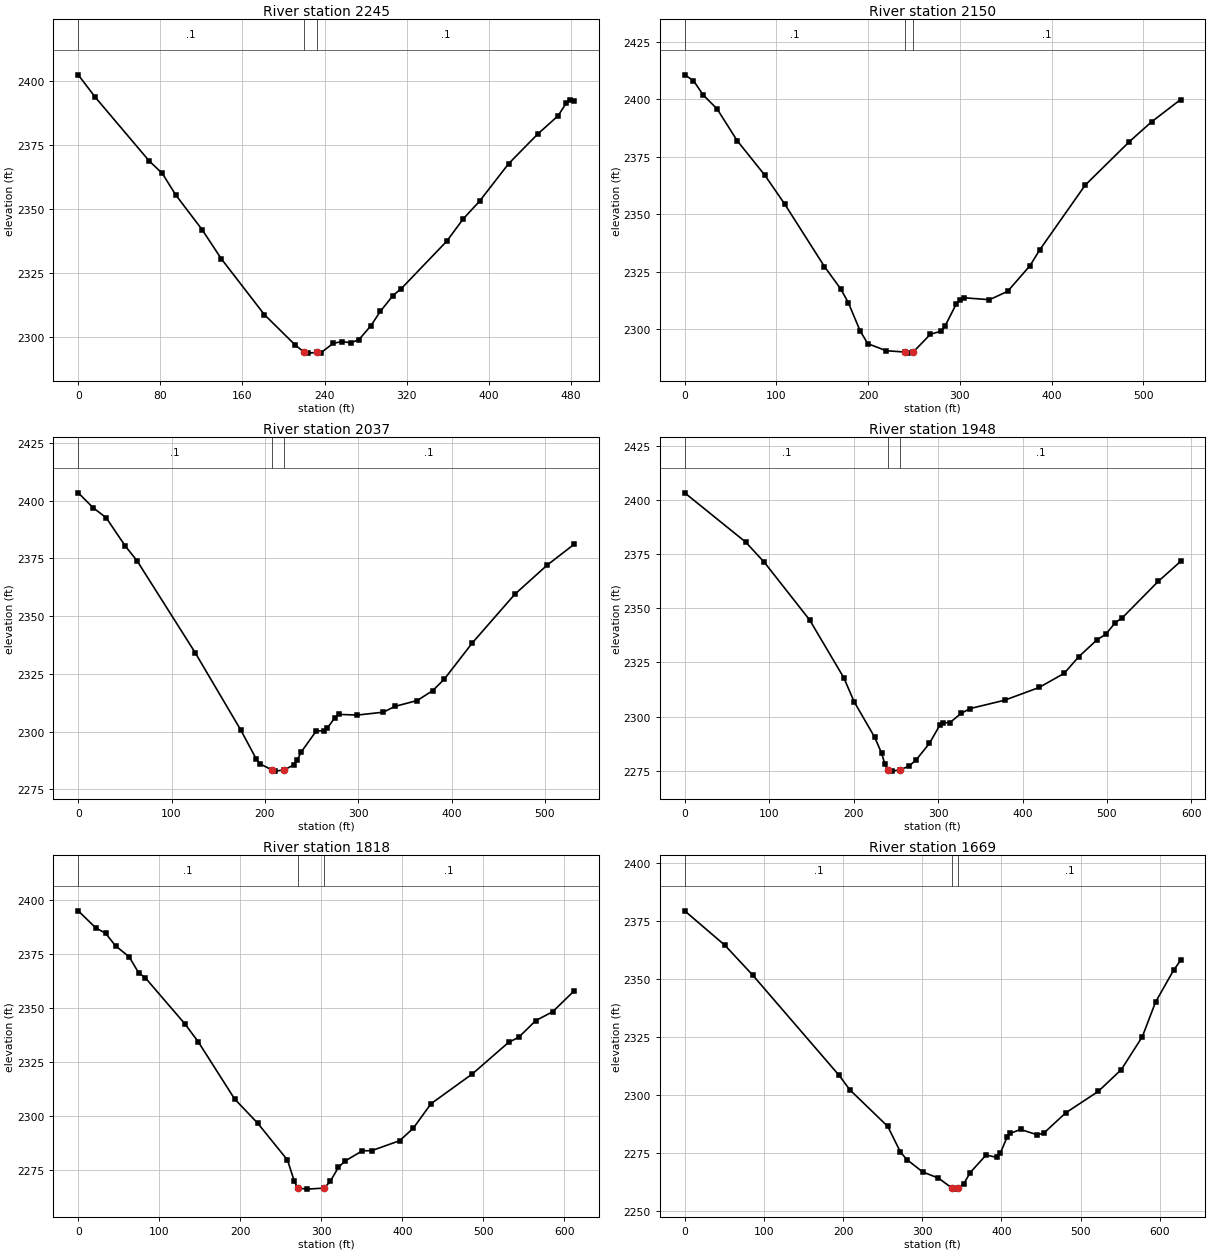
Type RM Length L Ch R = 1 ,2245    ,95.7,94.7,93.6
XS GIS Cut Line= 4
2335316.09838931700179.0528328282335127.26983577 700102.24121783
 2335029.4774736700074.7556462952334852.52005127700057.486058302
#Sta/Elev= 30
       0 2402.46    16.7 2393.67      69  2368.9      82 2363.94    94.9 2355.64
   120.8 2341.97   139.5 2330.59   181.3 2308.88   211.2 2297.07   220.2 2294.14
   223.7 2293.81     2332294.069   236.2 2293.91   248.6 2297.66   256.9  2298.3
   265.6 2297.86   273.5 2299.08   285.1 2304.46   294.3 2310.08   306.7 2316.29
   314.8 2319.01     359 2337.48   375.1  2346.2   391.1 2353.16   419.3 2367.74
   447.6  2379.3   467.5 2386.45   475.5 2391.41   479.6 2392.48   483.2 2392.32
#Mann= 3 ,-1,0
       0      .1       0   220.2    .045       0     233      .1       0
Bank Sta=220.2,233
XS Rating Curve= 0 ,0
Exp/Cntr(USF)=0,0
Exp/Cntr=0.3,0.1

Type RM Length L Ch R = 1 ,2150    ,112.6,112.9,111.1
XS GIS Cut Line= 4
2335353.04555853700082.5483094722335172.50534994700008.056367149
2335007.68042609699995.2544313162334828.73685834700015.779364996
#Sta/Elev= 30
       0 2410.61     9.6 2408.07    20.1 2401.89    35.4 2395.75    57.2    2382
    87.5  2366.9   108.9 2354.51   152.4 2327.24   170.2 2317.49   178.4 2311.56
   191.3 2299.27   199.6 2293.73   219.7 2290.65   240.4 2290.07   243.8 2289.61
  249.05 2290.04   267.9 2297.81   279.9  2299.2   283.9 2301.42   295.9 2310.83
   299.9 2312.76     304 2313.69   332.3 2312.84   352.1 2316.47   376.4 2327.58
   387.2 2334.57   436.6 2362.62   484.9 2381.58   509.1 2390.19   540.7 2399.86
#Mann= 3 ,-1,0
       0      .1       0   240.4    .045       0  249.05      .1       0
Bank Sta=240.4,249.05
XS Rating Curve= 0 ,0
Exp/Cntr(USF)=0,0
Exp/Cntr=0.3,0.1

Type RM Length L Ch R = 1 ,2037    ,91.2,89.2,88
XS GIS Cut Line= 4
2335369.17181149699947.784243243 2335186.6432186699901.788584051
2335006.84477145 699889.483457692334852.95750461699942.834790815
#Sta/Elev= 30
       0 2403.43    16.1 2396.93    29.9 2392.66    50.5 2380.34    62.9 2374.07
   125.3 2334.18   174.3 2300.57   190.7 2288.16   194.7 2286.05  207.722283.334
   210.8 2282.87   220.4 2283.35   230.8 2285.53   234.8 2287.78   238.8 2291.07
   254.8 2300.15   262.9 2300.46   266.9  2301.5   274.9 2306.02   278.9 2307.45
     299 2307.16     327 2308.41   339.1 2310.88   363.1 2313.45   379.8 2317.75
   392.3 2322.78   422.1 2338.36   467.8 2359.52   502.5 2372.15   531.3 2381.14
#Mann= 3 ,-1,0
       0      .1       0  207.72    .045       0   220.4      .1       0
Bank Sta=207.72,220.4
XS Rating Curve= 0 ,0
Exp/Cntr(USF)=0,0
Exp/Cntr=0.3,0.1

Type RM Length L Ch R = 1 ,1948    ,131.6,129.8,129.2
XS GIS Cut Line= 4
2335414.19928429699847.6841386972335182.29651747699809.625408801
2335005.27041827699837.0042599352334843.73622223699899.085511308
#Sta/Elev= 30
       0 2403.23    72.2 2380.51    94.5 2371.08     148 2344.54   188.4  2317.9
   200.7 2306.78     225 2290.41   233.1 2283.15   237.2 2277.88241.16322275.382
   245.2  2274.8255.12982275.402   265.5 2277.11   273.6 2279.77   289.8 2287.61
   301.9 2295.89     306 2297.08   314.1  2297.2   327.6 2301.55   338.3  2303.7
   378.8 2307.52   419.6  2313.4   449.2 2319.89   466.7 2327.63   488.2  2335.4
   498.7 2337.99   509.6 2343.23   518.2 2345.58     561 2362.47   587.2 2371.59
#Mann= 3 ,-1,0
       0      .1       0241.1632    .045       0255.1298      .1       0
Bank Sta=241.1632,255.1298
XS Rating Curve= 0 ,0
Exp/Cntr(USF)=0,0
Exp/Cntr=0.3,0.1

Type RM Length L Ch R = 1 ,1818    ,148.3,149.8,150.9
XS GIS Cut Line= 3
2335413.34907966699729.9489150622335159.90489757699678.778884931
2334822.99586517699785.846284532
#Sta/Elev= 30
       0 2394.98    21.6 2387.11    33.8 2384.58    46.1 2378.78    62.8 2373.73
    74.7 2366.25    82.8    2364   131.8 2342.62   148.1 2334.41     193 2307.97
   221.6  2296.7   258.3 2279.69   266.6 2269.99   270.9 2266.74   282.5 2266.24
   303.7 2266.73   311.2  2269.9   321.2 2276.38   329.6 2279.28   350.6 2283.96
   362.2 2284.03   396.8 2288.66   413.6 2294.44   435.4 2305.74   486.4 2319.53
   531.1  2334.1   543.7 2336.49   564.7  2344.2   585.7 2348.32   612.1 2357.96
#Mann= 3 ,-1,0
       0      .1       0   270.9    .045       0   303.7      .1       0
Bank Sta=270.9,303.7
XS Rating Curve= 0 ,0
Exp/Cntr(USF)=0,0
Exp/Cntr=0.3,0.1

Type RM Length L Ch R = 1 ,1669    ,93.7,93.6,94.1
XS GIS Cut Line= 4
2335410.18827776 699637.397940462335233.76159956 699554.58541804
2335060.21535692699549.5446558052334818.97887857699640.278376022
#Sta/Elev= 30
       0 2379.24    50.8 2364.42    86.2 2351.47   195.1 2308.43   208.5 2302.27
   256.5 2286.48   272.5 2275.45   280.5 2272.26   300.5 2266.92   320.5 2264.26
   337.8 2259.92   340.5 2259.52   345.6 2259.96   352.5 2261.84   360.6 2266.66
   380.7  2274.2   394.2 2273.16   398.5 2274.92     407 2281.78   411.3 2283.51
   424.1  2285.2   445.5 2282.86     454 2283.75   481.1 2292.31   522.4 2301.59
   551.5 2310.98     578 2325.14   594.7 2340.03   617.4 2353.68   626.3 2357.93
#Mann= 3 ,-1,0
       0      .1       0   337.8    .045       0   345.6      .1       0
Bank Sta=337.8,345.6
XS Rating Curve= 0 ,0
Exp/Cntr(USF)=0,0
Exp/Cntr=0.3,0.1

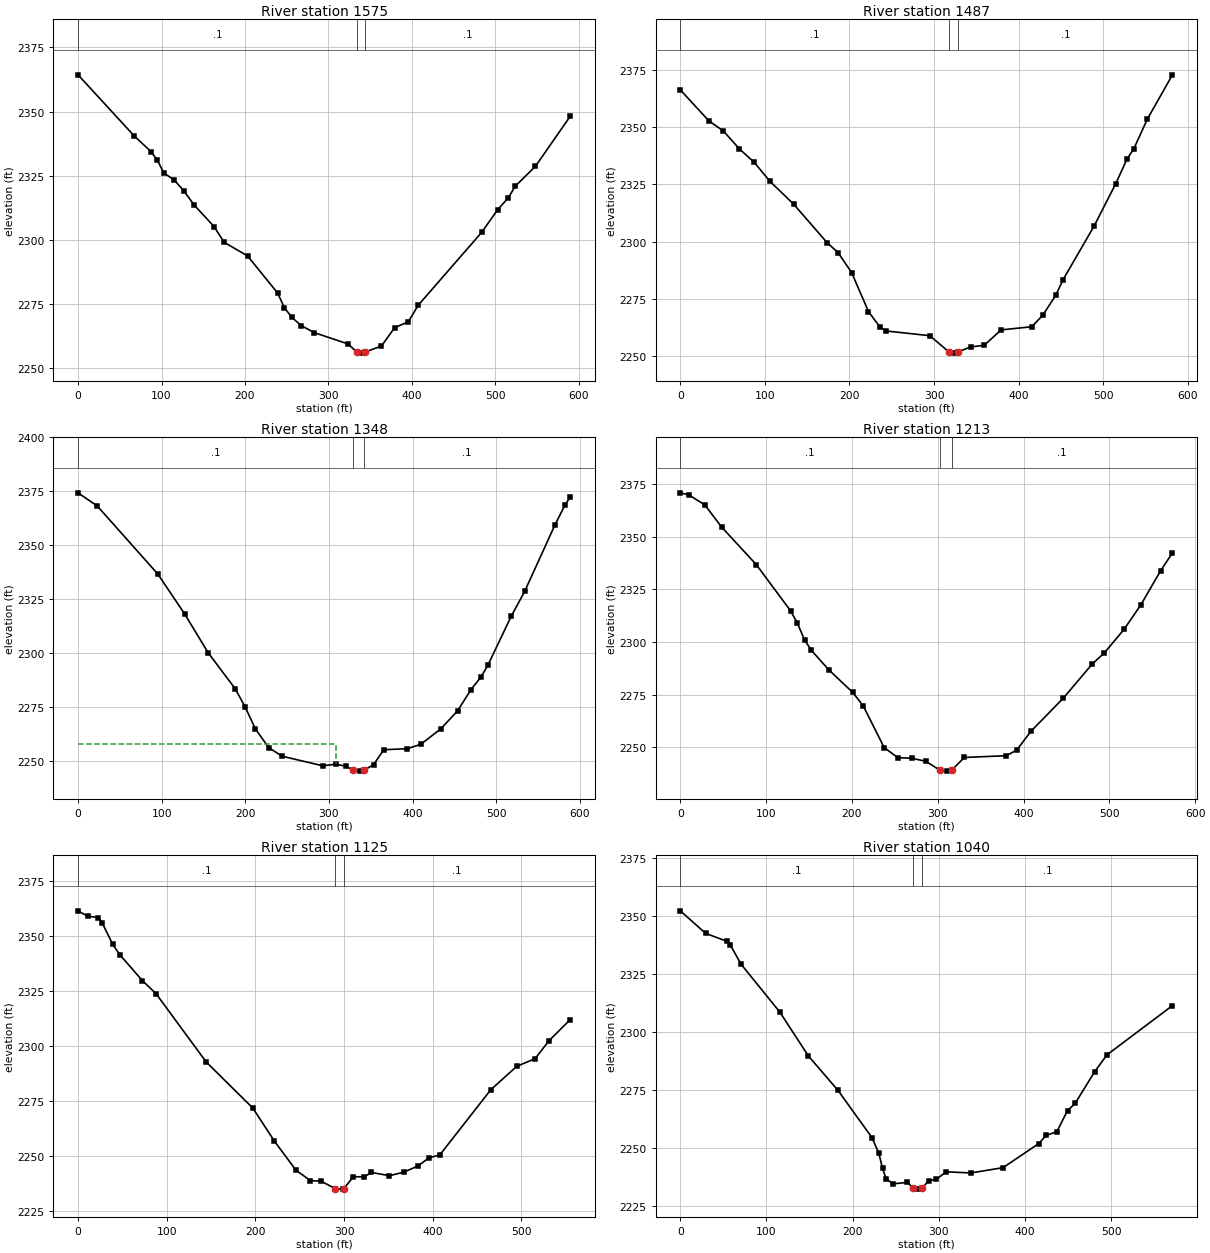
Type RM Length L Ch R = 1 ,1575    ,88.3,88.1,88.3
XS GIS Cut Line= 2
2335418.82958445699478.2538756352334830.50062082699440.808213323
#Sta/Elev= 30
       0 2364.31    67.6  2340.4    87.3 2334.43    94.8 2331.14   102.9 2326.02
   114.9 2323.43   126.9 2319.04   138.9 2313.65     163 2305.16     175 2299.05
   203.1 2293.73   239.1 2279.27   247.2 2273.58     256 2269.83   267.2 2266.61
   283.2 2263.83   323.3 2259.44  334.172256.248   339.3 2255.86   343.3 2256.24
   363.4 2258.61   379.4 2265.84   395.5    2268   407.5 2274.53   483.6 2302.96
   502.5 2311.69   515.4 2316.38   523.7  2320.9   547.8 2328.62   589.5 2348.11
#Mann= 3 ,-1,0
       0      .1       0  334.17    .045       0   343.3      .1       0
Bank Sta=334.17,343.3
XS Rating Curve= 0 ,0
Exp/Cntr(USF)=0,0
Exp/Cntr=0.3,0.1

Type RM Length L Ch R = 1 ,1487    ,140.5,139.1,137.4
XS GIS Cut Line= 2
2335421.71002001699403.3625510122334842.74247196699345.033730872
#Sta/Elev= 30
       0 2366.18    33.7 2352.68    50.9 2348.25    69.9  2340.4    87.4 2334.56
   106.1 2326.23   134.2 2316.24   173.6 2299.51   186.5 2295.21   202.6 2286.44
   222.5 2269.45   236.2 2262.64   242.8 2261.02     295 2258.93   317.5 2251.89
   323.2 2251.33   328.4 2251.87   343.3 2254.03   359.3 2254.74   379.4 2261.47
   415.6 2262.84   428.5 2267.84   443.8  2276.5   452.6  2283.4   489.2 2306.73
   514.7 2325.14   528.2 2336.02   536.2 2340.48   552.3 2353.49   581.9 2372.74
#Mann= 3 ,-1,0
       0      .1       0   317.5    .045       0   328.4      .1       0
Bank Sta=317.5,328.4
XS Rating Curve= 0 ,0
Exp/Cntr(USF)=0,0
Exp/Cntr=0.3,0.1

Type RM Length L Ch R = 1 ,1348    ,131.2,134.4,136.2
XS GIS Cut Line= 4
2335431.03154955699250.465151803 2335161.7507105 699224.05543725
2335068.13655472699240.6179417342334845.97156867699223.126496061
#Sta/Elev= 30
       0 2374.25      23 2368.15    95.3 2336.68   127.5 2318.15   155.6 2300.17
   187.8 2283.57   199.8 2275.11   211.9 2265.04   227.9 2256.26     244 2252.24
   292.5 2247.81   308.7 2248.54   320.9 2247.53     329  2245.7   337.2 2245.33
   341.9 2245.69   353.4 2248.31   365.6 2255.24   393.7 2255.73   409.8 2257.73
   433.8 2264.92   453.9 2273.26   469.9  2283.1     482 2289.01     490 2294.31
   518.1 2317.14   534.1 2328.59   570.2  2359.3   582.3  2368.6   588.5 2372.27
#Mann= 3 ,-1,0
       0      .1       0     329    .045       0   341.9      .1       0
#XS Ineff= 2 , 0
          308.45  2258.1
Permanent Ineff=
       F       F
Bank Sta=329,341.9
XS Rating Curve= 0 ,0
Exp/Cntr(USF)=0,0
Exp/Cntr=0.3,0.1

Type RM Length L Ch R = 1 ,1213    ,89.7,88.5,88.4
XS GIS Cut Line= 4
2335424.59045557699140.5228059392335188.39473945699121.799974783
2335033.57132797699090.1151835962334858.58486755699126.120628126
#Sta/Elev= 30
       0 2370.77     9.9 2369.81    28.5 2365.07    48.1 2354.54    88.7 2336.62
   128.8 2314.61   136.3 2308.97   144.9 2300.87   152.9 2295.95     173 2286.76
     201    2276   213.1  2269.7   237.6 2249.84   253.5 2245.05   269.8 2244.77
   286.2 2243.31   302.5 2239.09   310.7 2238.65  316.172239.046   331.1 2245.15
   380.1 2245.97   392.3 2248.73   408.6 2257.53   446.2  2273.2     480 2289.46
   494.4 2294.86   517.3 2306.03   536.8 2317.59   559.7 2333.73   573.6 2342.27
#Mann= 3 ,-1,0
       0      .1       0   302.5    .045       0  316.17      .1       0
Bank Sta=302.5,316.17
XS Rating Curve= 0 ,0
Exp/Cntr(USF)=0,0
Exp/Cntr=0.3,0.1

Type RM Length L Ch R = 1 ,1125    ,84.6,85,85.4
XS GIS Cut Line= 3
2335410.90838665699065.6314813152335014.12838792699001.541790051
2334865.78595646699039.707561253
#Sta/Elev= 30
       0 2361.42    10.9 2358.97      23 2358.38    27.1 2356.08    39.2 2346.15
    47.3 2341.42    72.5 2329.76    87.9 2323.86   144.6 2292.77   197.3  2271.8
   221.6 2256.77   245.9 2243.61   262.1 2238.93   274.2 2238.62   290.4 2235.25
   298.6 2235.05  299.742235.305   310.7 2240.67   322.9 2240.65     331 2242.62
   351.2 2241.16   367.4 2242.73   383.6 2245.61   395.8 2249.25   408.1  2250.6
   465.6 2280.19   494.8  2290.8   515.5 2294.28   531.3 2302.44   555.1 2312.01
#Mann= 3 ,-1,0
       0      .1       0   290.4    .045       0  299.74      .1       0
Bank Sta=290.4,299.74
XS Rating Curve= 0 ,0
Exp/Cntr(USF)=0,0
Exp/Cntr=0.3,0.1

Type RM Length L Ch R = 1 ,1040    ,102.7,100.1,97.2
XS GIS Cut Line= 3
2335400.82686218698997.2211367072335055.17459469698916.568940959
 2334847.0631253698975.617869989
#Sta/Elev= 30
       0 2352.22    29.4 2342.49    53.9 2339.11    58.2 2337.37    70.5 2329.21
   115.7 2308.46   148.5 2289.71     183 2274.79   222.5 2254.39   230.4  2247.7
   234.8 2241.08   238.9  2236.6   247.1 2234.46   263.5 2235.09   270.3  2232.7
   275.9 2232.18  280.932232.653   288.2 2235.83     297 2236.34   308.7 2239.64
   337.5 2239.16   374.7 2241.45   416.2 2251.86   424.6 2255.33   437.1 2256.94
   449.5 2266.07   458.3 2269.13   480.9 2282.78   495.3 2290.11   571.3 2311.34
#Mann= 3 ,-1,0
       0      .1       0   270.3    .045       0  280.93      .1       0
Bank Sta=270.3,280.93
XS Rating Curve= 0 ,0
Exp/Cntr(USF)=0,0
Exp/Cntr=0.3,0.1

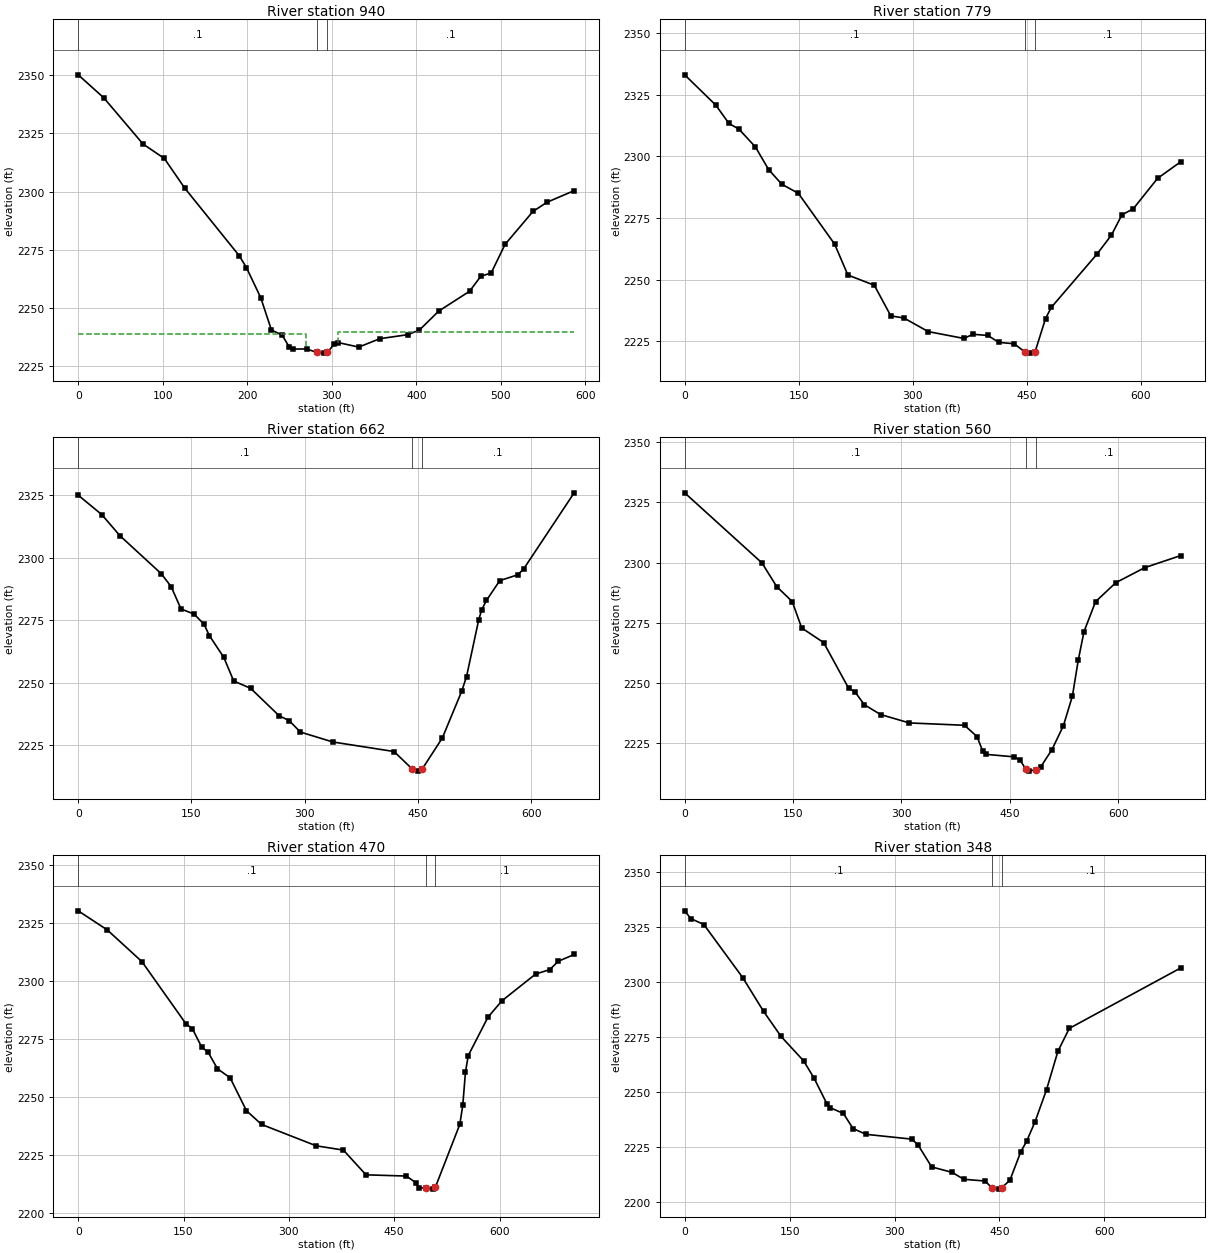
Type RM Length L Ch R = 1 ,940     ,165.2,161.2,161
XS GIS Cut Line= 3
2335408.74805998698901.4466542562335180.47354166698824.395002961
2334844.90279863698907.927634272
#Sta/Elev= 30
       0 2350.12    30.2 2340.27    76.6 2320.44   101.9 2314.22   125.9 2301.55
   190.6 2272.42     199 2267.38   215.9 2254.49   228.6 2240.57   241.2 2238.42
   249.5  2233.4   253.6 2232.41   270.1 2232.46   282.5 2230.96   290.7 2230.67
   294.8 2230.99   303.1 2234.68   307.2 2235.23   331.9 2233.26   356.7 2236.86
   389.6 2238.58   403.5 2240.53   426.6 2248.74     463 2257.22   476.2 2263.62
   488.6 2265.11     505 2277.36     538 2291.49   554.5 2295.41   586.7 2300.41
#Mann= 3 ,-1,0
       0      .1       0   282.5    .045       0   294.8      .1       0
#XS Ineff= 2 , 0
           269.6 2238.92  307.28          2239.7
Permanent Ineff=
       F       F
Bank Sta=282.5,294.8
XS Rating Curve= 0 ,0
Exp/Cntr(USF)=0,0
Exp/Cntr=0.3,0.1

Type RM Length L Ch R = 1 ,779     ,114,116.7,122.1
XS GIS Cut Line= 4
2335405.86762442 698788.389558432335122.86483041698668.131373698
2334986.04414119698765.3460739312334826.17996747698842.397725226
#Sta/Elev= 30
       0 2333.09      41 2320.79    58.3 2313.35    71.4 2311.07    93.1 2303.85
   110.5 2294.66   127.9  2288.7   149.6 2285.04   197.4 2264.42   214.8  2251.9
   249.6 2247.75   271.3 2235.33   288.7 2234.45   320.6 2228.95   367.5 2226.18
   379.5 2227.87   399.1 2227.38   413.4 2224.59   433.6 2224.02   447.4 2220.81
   454.3 2220.22   461.2 2220.73     475 2234.25   482.6 2238.78   542.5  2260.3
   561.8 2268.12   575.5 2276.29   590.5 2278.77   622.4 2291.08   652.8  2297.8
#Mann= 3 ,-1,0
       0      .1       0   447.4    .045       0   461.2      .1       0
Bank Sta=447.4,461.2
XS Rating Curve= 0 ,0
Exp/Cntr(USF)=0,0
Exp/Cntr=0.3,0.1

Type RM Length L Ch R = 1 ,662     ,101.3,101.5,101.5
XS GIS Cut Line= 3
2335400.82686218698745.1830249942335165.35125495698642.207453636
2334765.69082066698642.927562527
#Sta/Elev= 30
       0 2325.12    31.3 2317.32    55.2 2308.92   109.9 2293.72     123 2288.57
   136.1 2279.61   153.5 2277.53   166.6 2273.49   173.6 2268.97   192.8 2260.21
   205.9 2250.77   228.3 2247.85   266.2 2236.83   279.3 2234.94   294.2 2230.35
     337 2226.39   418.2 2222.56   442.2  2215.6   450.2 2214.72   455.6  2215.6
   482.2 2228.02   507.7  2246.6   514.2 2252.54   530.2 2275.08   534.2 2279.21
   540.6 2283.05   558.2 2290.93   582.2 2293.28   590.2 2295.77   656.7 2326.06
#Mann= 3 ,-1,0
       0      .1       0   442.2    .045       0   455.6      .1       0
Bank Sta=442.2,455.6
XS Rating Curve= 0 ,0
Exp/Cntr(USF)=0,0
Exp/Cntr=0.3,0.1

Type RM Length L Ch R = 1 ,560     ,87.5,90.7,92.3
XS GIS Cut Line= 3
2335421.71002001698698.3759471042335047.25339689698542.112317841
2334766.41092955698538.511773388
#Sta/Elev= 30
       0 2329.02     107 2299.83   127.4 2289.97   148.9 2283.74     162 2272.75
   192.4 2266.66     227 2247.62   235.7 2246.17   248.7 2240.79   271.2  2236.7
     311  2233.2   387.4 2232.22   404.8 2227.49   412.8 2221.31   416.8 2220.12
   456.6 2219.07   464.7 2217.57  472.362213.893   476.8 2213.13   486.32213.783
   492.8 2214.81   508.5 2222.11   524.3 2232.01   536.8  2244.4   544.8  2259.2
   552.8 2271.19   568.8 2283.68   596.8 2291.59   636.9 2297.86   686.6 2302.88
#Mann= 3 ,-1,0
       0      .1       0  472.36    .045       0   486.3      .1       0
Bank Sta=472.36,486.3
XS Rating Curve= 0 ,0
Exp/Cntr(USF)=0,0
Exp/Cntr=0.3,0.1

Type RM Length L Ch R = 1 ,470     ,119.5,121.2,123.3
XS GIS Cut Line= 3
2335429.17376066698678.0772054672334977.66548625698449.802687144
2334777.47521466698446.202142691
#Sta/Elev= 30
       0 2330.19    41.5 2321.94    90.8 2308.28   153.5 2281.49   162.5 2279.46
   175.9 2271.46   184.9 2269.33   198.3 2262.16   216.3 2258.27   239.6 2244.09
   261.1 2238.18   338.9 2228.98   377.6 2227.13   409.8 2216.48   467.3 2215.95
   480.7  2213.1   485.2 2210.75   495.6 2210.97   504.5 2210.32  508.45 2211.05
   543.4 2238.23   547.6 2246.41   551.4 2260.66   555.4 2267.84   583.4 2284.35
   603.4 2291.45   651.4 2302.97   671.5 2304.87   683.5 2308.45   706.2 2311.38
#Mann= 3 ,-1,0
       0      .1       0   495.6    .045       0  508.45      .1       0
Bank Sta=495.6,508.45
XS Rating Curve= 0 ,0
Exp/Cntr(USF)=0,0
Exp/Cntr=0.3,0.1

Type RM Length L Ch R = 1 ,348     ,96.5,93,89.1
XS GIS Cut Line= 4
2335419.77231651698586.2243965922335124.68083137 698413.08398439
2335016.27987764 698327.266562692334791.95012618698370.928057941
#Sta/Elev= 30
       0 2332.47     8.8 2328.93    27.4 2326.23      83 2302.04   112.7 2286.69
   137.8 2275.23     170 2264.12     185  2256.2   203.6 2244.36   208.2 2242.74
   226.8 2240.16   240.7 2233.27   259.2 2230.64   324.9 2228.44   333.7 2225.75
     353 2215.79   382.3  2213.3   398.9 2210.16   429.5 2209.36   439.2 2206.22
   449.9 2205.67  452.942206.204   464.9 2209.74   480.5 2222.75   488.7  2227.4
   500.9 2236.44   517.2 2250.94   533.5 2268.49   549.8 2278.91   708.9 2306.42
#Mann= 3 ,-1,0
       0      .1       0   439.2    .045       0  452.94      .1       0
Bank Sta=439.2,452.94
XS Rating Curve= 0 ,0
Exp/Cntr(USF)=0,0
Exp/Cntr=0.3,0.1

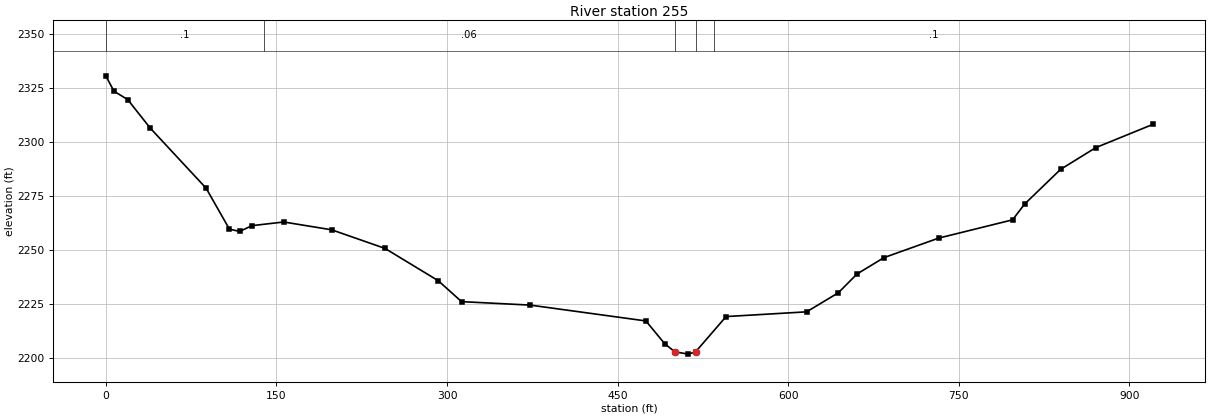
Type RM Length L Ch R = 1 ,255     ,93,93.1,93.1
XS GIS Cut Line= 6
2335481.83247428698560.2691884862335464.93938056698452.841962241
 2335246.0296581698319.2986690892335000.67770522698252.072234001
2334823.29953191698241.1305837222334743.89318821698335.789331968
#Sta/Elev= 30
       0 2330.52     7.2  2323.4    19.3  2319.5    39.1  2306.3    88.2 2278.48
   108.7 2259.49   117.8 2258.43   128.4 2261.11   156.5 2262.81   198.7 2259.18
   245.5 2250.57   292.3 2235.61   312.8 2225.92   373.2 2224.31   474.9 2216.97
   491.5 2206.37  500.38 2202.66   512.3  2201.6   518.62202.675   545.4    2219
   616.2 2221.19   644.1 2230.02   660.5 2238.72   684.2  2246.3   732.2 2255.33
   797.3 2263.81   807.8 2271.08   839.5 2287.19   870.4 2297.25   920.8 2308.06
#Mann= 5 ,-1,0
       0      .1       0  138.75     .06       0  500.38    .045       0
   518.6     .06       0  535.18      .1       0
Bank Sta=500.38,518.6
XS Rating Curve= 0 ,0
Exp/Cntr(USF)=0,0
Exp/Cntr=0.3,0.1