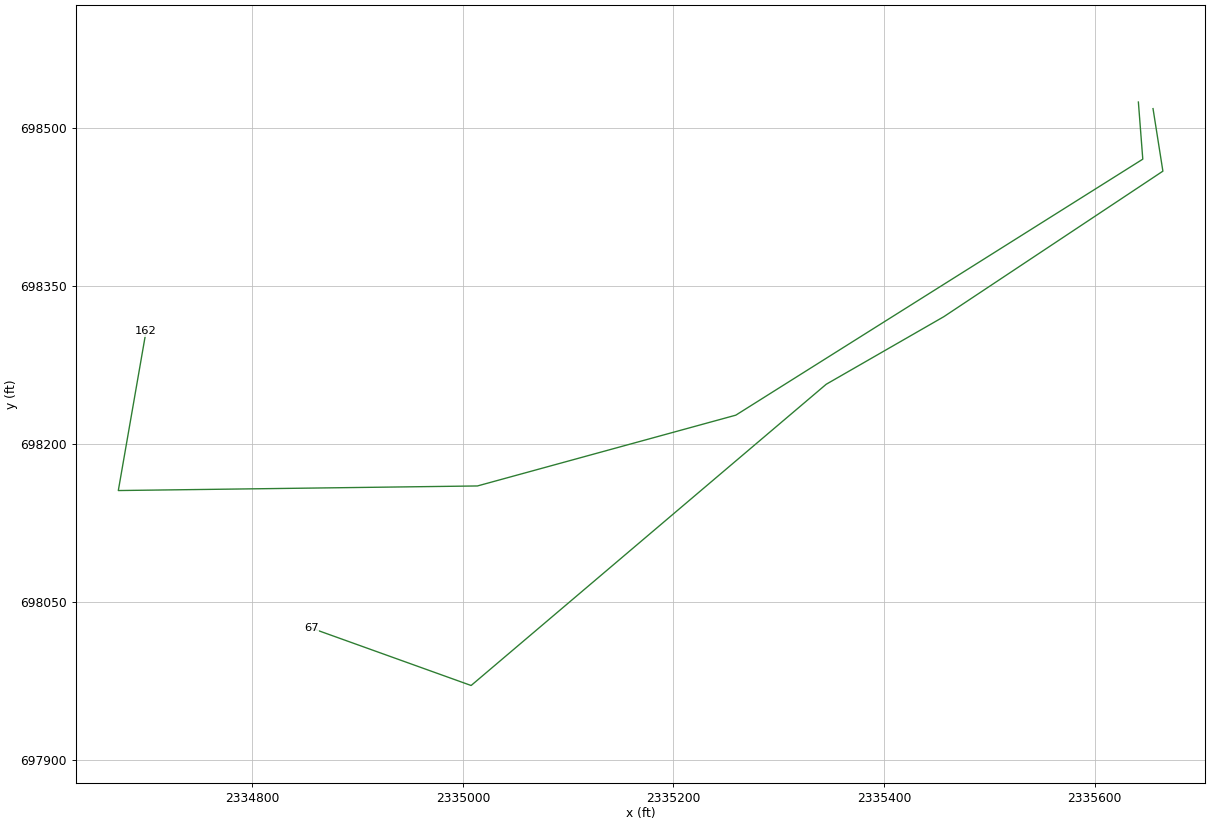
HEC-RAS study BCKLERN.prj: BCKLERN

--- BCKLERN.g01 (geometry) --- (continued)

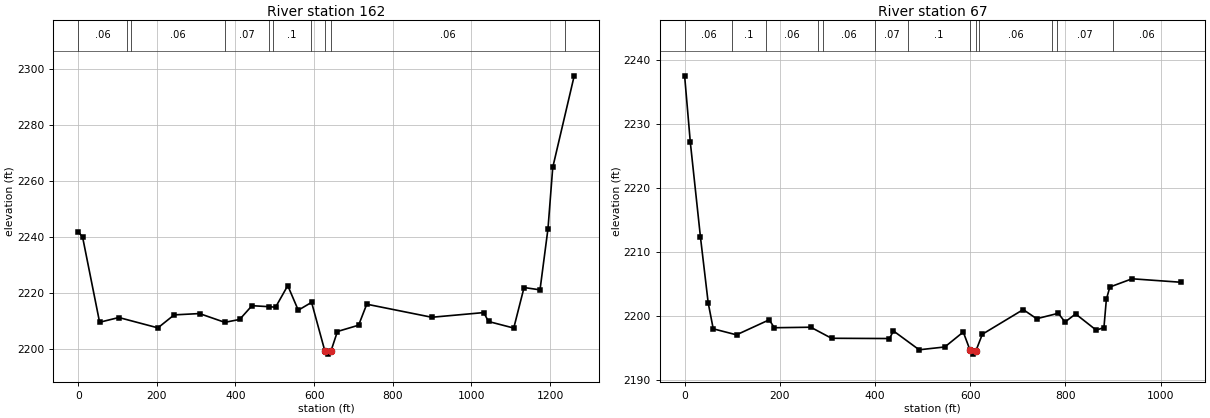
Type RM Length L Ch R = 1 ,162     ,90.4,95.5,98.5
XS GIS Cut Line= 6
2335641.47483914698524.3447520262335645.66388499 698470.10142878
2335259.17314439698226.9956177642335013.82119151698159.769182676
2334672.79677377698155.413843584 2334699.1806275698306.941068876
#Sta/Elev= 30
       0 2241.95    11.2 2239.93    54.4  2209.6   103.4 2211.29   202.7  2207.6
     244 2212.23   308.5  2212.7   372.8 2209.57   410.6  2210.6     442 2215.51
   484.4 2215.16     502 2214.97     533 2222.67   559.7  2213.9   593.6  2216.7
  627.232199.415   634.4 2198.23  643.042199.395   659.3  2206.3   713.2 2208.55
   733.9 2216.04   899.3 2211.38  1031.5 2213.05  1043.6 2209.87  1107.8 2207.53
    1134 2221.99  1174.6 2221.16  1194.9 2242.99    1207 2264.84  1261.6 2297.51
#Mann= 10 ,-1,0
       0     .06       0   124.4      .1       0   134.4     .06       0
   374.4     .07       0   484.4     .06       0   494.4      .1       0
     591     .06       0  627.23    .045       0  643.04     .06       0
  1237.8      .1       0
Bank Sta=627.23,643.04
XS Rating Curve= 0 ,0
Exp/Cntr(USF)=0,0
Exp/Cntr=0.3,0.1

Type RM Length L Ch R = 1 ,67      ,,,
XS GIS Cut Line= 6
2335655.38111425698518.0980717852335664.75128423698458.712517841
2335456.74763551698320.5372923292335345.03535587698256.340240196
2335007.83286473697970.2827595062334856.21230142698024.727096067
#Sta/Elev= 30
       0 2237.53      12 2227.11    33.3 2212.27    49.5 2202.02    60.1 2197.94
     109    2197   177.7 2199.35   188.5 2198.11     265 2198.19   308.7 2196.46
   430.4 2196.42   438.7 2197.61   492.7 2194.66   546.6  2195.1   585.4 2197.44
  599.87 2194.55   606.3 2193.98     612  2194.5   625.4 2197.09   711.3 2200.95
   739.6 2199.52     785 2200.37   799.2    2199   821.4 2200.27   864.6 2197.74
   880.9 2198.13     886 2202.55   893.3 2204.48     940 2205.77    1042 2205.23
#Mann= 13 ,-1,0
       0     .06       0  100.12      .1       0  170.12     .06       0
  279.75      .1       0  289.75     .06       0  399.84     .07       0
  468.68      .1       0  599.87    .045       0     612      .1       0
   618.9     .06       0   771.4    .025       0   781.4     .07       0
   900.9     .06       0
Bank Sta=599.87,612
XS Rating Curve= 0 ,0
Exp/Cntr(USF)=0,0
Exp/Cntr=0.3,0.1
LCMann Table=0

Chan Stop Cuts=-1
Use User Specified Reach Order=0
Composite Channel Slope=5